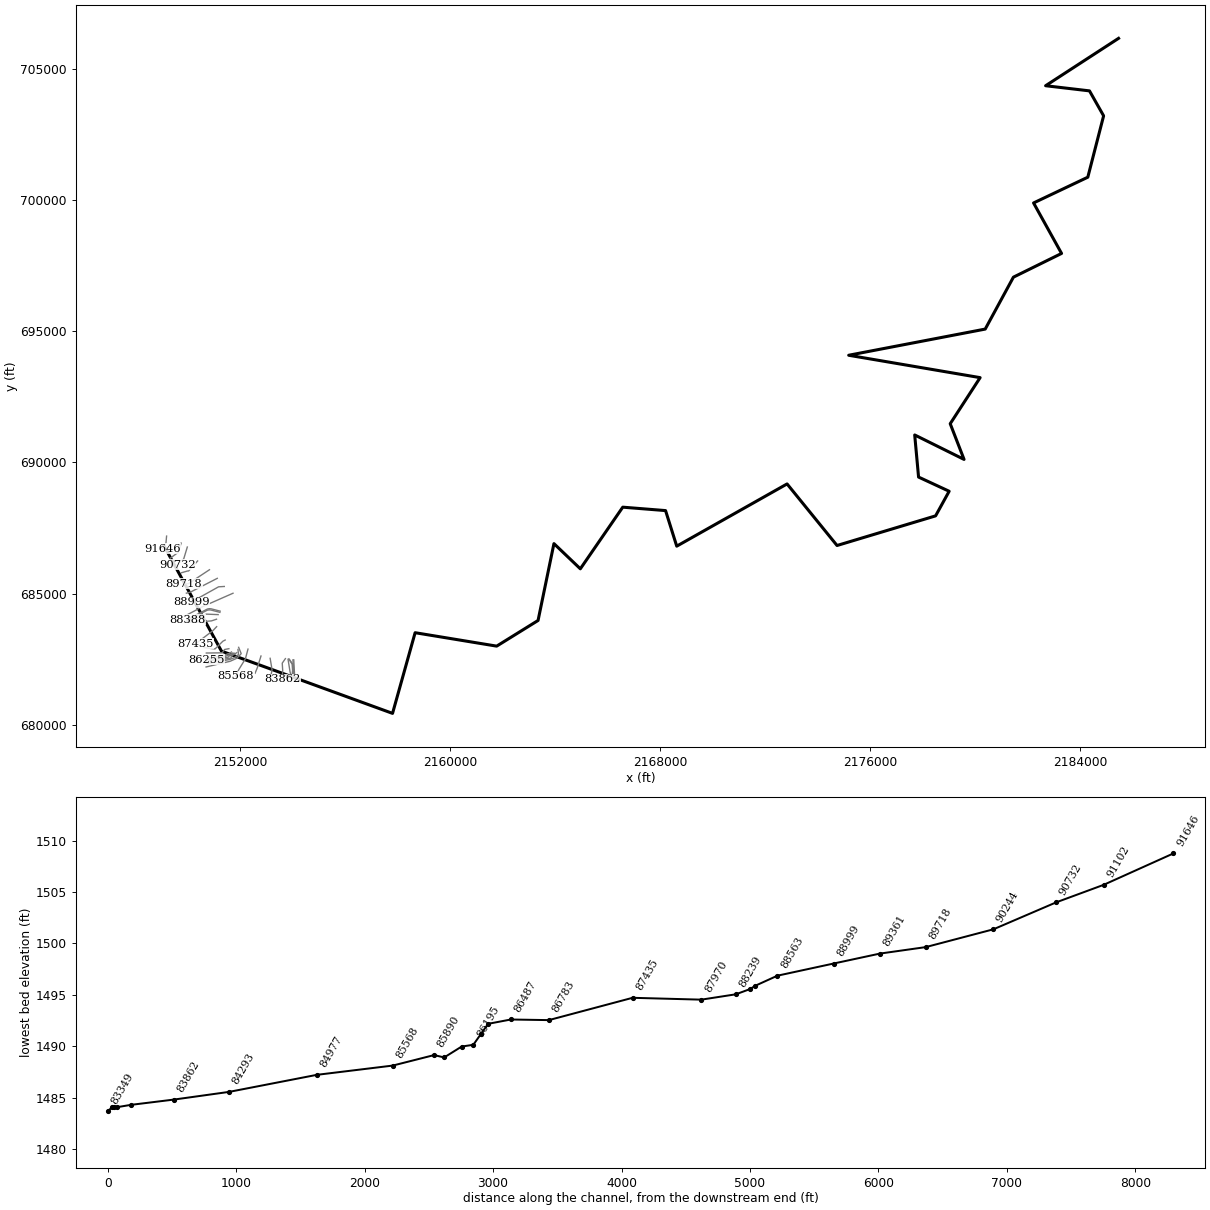
--- FRENCHCK.prj (project) ---

Proj Title=FRENCHCK
Current Plan=p01
Default Exp/Contr=0,0
English Units
Geom File=g01
Flow File=f01
Plan File=p01
BEGIN DESCRIPTION:
---------- MODELED AS PART OF WVEMD CTP PROGRAM, 2023----------
Stream Name: French Creek
Flood Zone:  AFH
Upshur County, WV
HEC-RAS Version: RAS 6.3
Vertical Datum: NAVD88
Projection: NAD 1983 StatePlane West Virginia S FIPS 4702 (US Feet)
Terrain: 1-meter LIDAR (FEMA Region III 3DEP collected 2016-2018)
Land Use: 2019 NLCD
Hydrologic Method:
WV SIR2010-5033 regression equations
Additional Model Notes:
Between RS 85890 - 85968 there is flow on the ROB that diverts into WFORKRV
END DESCRIPTION:
DSS Export Rating Curves= 0
DSS Export Rating Curve Sorted= 0
DSS Export Volume Flow Curves= 0
DXF OffsetX= 0
DXF OffsetY= 0
DXF ScaleX= 0
DXF ScaleY= 0

--- FRENCHCK.p01 (plan) ---

Plan Title=Floodplain
Program Version=6.31
Short Identifier=Floodplain
Geom File=g01
Flow File=f01
Subcritical Flow
K Sum by GR= 0
Std Step Tol= 0.01
Critical Tol= 0.01
Num of Std Step Trials= 20
Max Error Tol= 0.3
Flow Tol Ratio= 0.001
Split Flow NTrial= 30
Split Flow Tol= 0.02
Split Flow Ratio= 0.02
Log Output Level= 0
Friction Slope Method= 1
Unsteady Friction Slope Method= 2
Unsteady Bridges Friction Slope Method= 1
Parabolic Critical Depth
Global Vel Dist= 0 , 0 , 0
Global Log Level= 0
CheckData=True
Encroach Param=-1 ,0,0, 0
Mapping Interval=1HOUR
Computation Time Step Use Courant=        0
Computation Time Step Use Time Series=    0
Computation Time Step Count To Double=0
Computation Time Step Max Doubling=0
Computation Time Step Max Halving=0
Computation Time Step Residence Courant=0
Run HTab= 0
Run UNet= 0
Run Sediment= 0
Run PostProcess= 0
Run WQNet= 0
Run RASMapper=-1
UNET Theta= 0
UNET Theta Warmup= 0
UNET ZTol= 0
UNET ZSATol= 0
UNET MxIter= 0
UNET Max Iter WO Improvement= 0
UNET MaxInSteps= 0
UNET DtIC= 0
UNET DtMin= 0
UNET MaxCRTS= 0
UNET WFStab= 0
UNET SFStab= 0
UNET WFX= 1
UNET SFX= 1
UNET Gravity=32.17405
UNET 1D Methodology=Finite Difference
UNET DSS MLevel= 1
UNET Pardiso=0
UNET DZMax Abort= 0
UNET Use Existing IB Tables= 0
UNET Froude Reduction=False
UNET Froude Limit= 0
UNET Froude Power= 0
UNET D1 Cores= 0
UNET WindReference=Eulerian
UNET WindDragFormulation=Hsu (1988)
UNET D2 Coriolis=0
UNET D2 Cores= 0
UNET D2 Theta= 1
UNET D2 Theta Warmup= 1
UNET D2 Z Tol= 0.01
UNET D2 Volume Tol= 0.01
UNET D2 Max Iterations= 20
UNET D2 Equation= 0
UNET D2 RampUpFraction=0.1
UNET D2 TimeSlices= 1
UNET D2 Turbulence Formulation=Non-Conservative (original)
UNET D2 Eddy Viscosity=0.3
UNET D2 Transverse Eddy Viscosity=0.1
UNET D2 Smagorinsky Mixing=0
UNET D2 BCVolumeCheck=0
UNET D2 Cores=0
UNET D2 SolverType=PARDISO (Direct)
UNET D2 Minimum Iterations= 3
UNET D2 Maximum Iterations= 30
UNET D2 Restart Number= 10
UNET D2 Relaxation Coeff=1.3
UNET D2 SOR Precondition Iterations= 10
UNET D2 ILUT Maximum Fill= 8
UNET D2 ILUT Tolerance=1E-08
UNET D2 Convergence Tolerance=0.00001
UNET D1D2 MaxIter= 0
UNET D1D2 ZTol=0.01
UNET D1D2 QTol=0.1
UNET D1D2 MinQTol=1
Write IC File= 0
Write IC File at Fixed DateTime=0
Write IC File at Sim End=0
Echo Input=False
Echo Parameters=False
Echo Output=False
Write Detailed= 0
HDF Write Warmup=0
HDF Write Time Slices=0
HDF Flush=0
HDF Compression= 1
HDF Chunk Size= 1
HDF Spatial Parts= 1
HDF Use Max Rows=0
HDF Fixed Rows= 1
Calibration Method= 0
Calibration Iterations= 20
Calibration Max Change=0.05
Calibration Tolerance=0.2
Calibration Maximum=1.5
Calibration Minimum=0.5
Calibration Optimization Method= 1
WQ AD Non Conservative
WQ ULTIMATE=-1
WQ Max Comp Step=1HOUR
WQ Output Interval=15MIN
WQ Output Selected Increments= 0
WQ Create Restart=0
WQ Fixed Restart=0
WQ System Summary=0
WQ Write To DSS=0
Sorting and Armoring Iterations= 10
XS Update Threshold= 0.02
Bed Roughness Predictor= 0
Hydraulics Update Threshold= 0.02
Energy Slope Method= 1
Volume Change Method= 1
Sediment Retention Method= 0
Sediment TS Multiplier= 1
Warm Up Method= 0
XS Weighting Method= 0
Number of US Weighted Cross Sections= 1
Number of DS Weighted Cross Sections= 1
Upstream XS Weight=0
Main XS Weight=1
Downstream XS Weight=0
Number of DS XS's Weighted with US Boundary= 1
Upstream Boundary Weight= 1
Weight of XSs Associated with US Boundary= 0
Number of US XS's Weighted with DS Boundary= 1
Downstream Boundary Weight= 0.5
Weight of XSs Associated with DS Boundary= 0.5
Percentile Method= 0
Sediment Output Level= 3
Mass or Volume Output= 0
Output Increment Type= 1
Profile and TS Output Increment= 1
Transport Output Increment 1
XS Output Flag= 0
XS Output Increment= 10
Read HDF5 Sediment Hotstart= 0
Sediment Hotstart Type= 0
Write Gradation File= 0
Read Gradation Hotstart= 0
Write HDF5 File= 1
Write Binary Output= 1
Write DSS Sediment File= 0
DSS Sediment Output Type= 1
SV Curve= 0
Specific Gage Flag= 0
Subcell Erosion Methods= 0
Subcell Deposition Methods= 0
Advection Scheme= 1
Matrix Solver= 0
Implicit Weighting Factor= 1
Maximum Outer Loop Convergence Iterations= 5
Convergence Maximum Absolute= 0.001
Convergence RMSE= 0.0001
Grain Fractions Max Abs Error= 0.001
Max Subgrid Regions= 1
Max Subgrid Length Scale= 3.402823E+38
Initial Layer Thickness= 3.402823E+38
Min Layer Thickness= 3.402823E+38
Max Layer Thickness= 3.402823E+38
Number of Layers= 5

--- FRENCHCK.f01 (steady flow) ---

Flow Title=Flows
Program Version=6.31
Number of Profiles= 1
Profile Names=01pct
River Rch & RM=FRENCHCK,Main,91646
     305
River Rch & RM=FRENCHCK,Main,88563
     345
River Rch & RM=FRENCHCK,Main,87435
     388
River Rch & RM=FRENCHCK,Main,86487
     441
River Rch & RM=FRENCHCK,Main,85568
     632
River Rch & RM=FRENCHCK,Main,82457
     703
River Rch & RM=FRENCHCK,Main,79081
    1230
River Rch & RM=FRENCHCK,Main,74617
    1410
River Rch & RM=FRENCHCK,Main,71094
    1610
River Rch & RM=FRENCHCK,Main,63863
    2530
River Rch & RM=FRENCHCK,Main,56255
    3010
River Rch & RM=FRENCHCK,Main,52739
    3350
River Rch & RM=FRENCHCK,Main,42865
    4970
River Rch & RM=FRENCHCK,Main,35227
    5670
River Rch & RM=FRENCHCK,Main,26607
    6680
Boundary for River Rch & Prof#=FRENCHCK,Main            , 1
Up Type= 0
Dn Type= 3
Dn Slope=0.00035
DSS Import GetInterval= 0
DSS Import GetPeak= 0
DSS Import FillOption= 0

--- FRENCHCK.g01 (geometry) ---

Geom Title=Geometry
Program Version=6.31

River Reach=FRENCHCK        ,Main
Reach XY= 30
2149109.12090264686819.022805288     2151294.157      682810.675
     2157810.652      680437.517     2158670.803      683512.491
      2161777.37      683000.573     2163353.589      683978.624
      2163958.74      686908.484     2164963.719      685947.861
     2166580.287      688297.266     2168210.162      688166.947
     2168635.745      686810.902     2172838.577      689183.287
     2174741.595       686836.17     2178495.693      687965.745
     2179012.305       688903.79     2177847.303      689444.468
     2177700.043      691049.876      2179579.94      690117.469
     2179052.797       691478.35     2180192.073      693234.823
     2175185.035      694087.706     2180385.892      695085.216
      2181460.18       697064.44     2183293.889       697968.89
     2182227.442      699893.056     2184293.774      700874.741
     2184895.892      703213.558     2184357.732      704165.139
     2182686.449      704361.104     2185464.957      706167.599

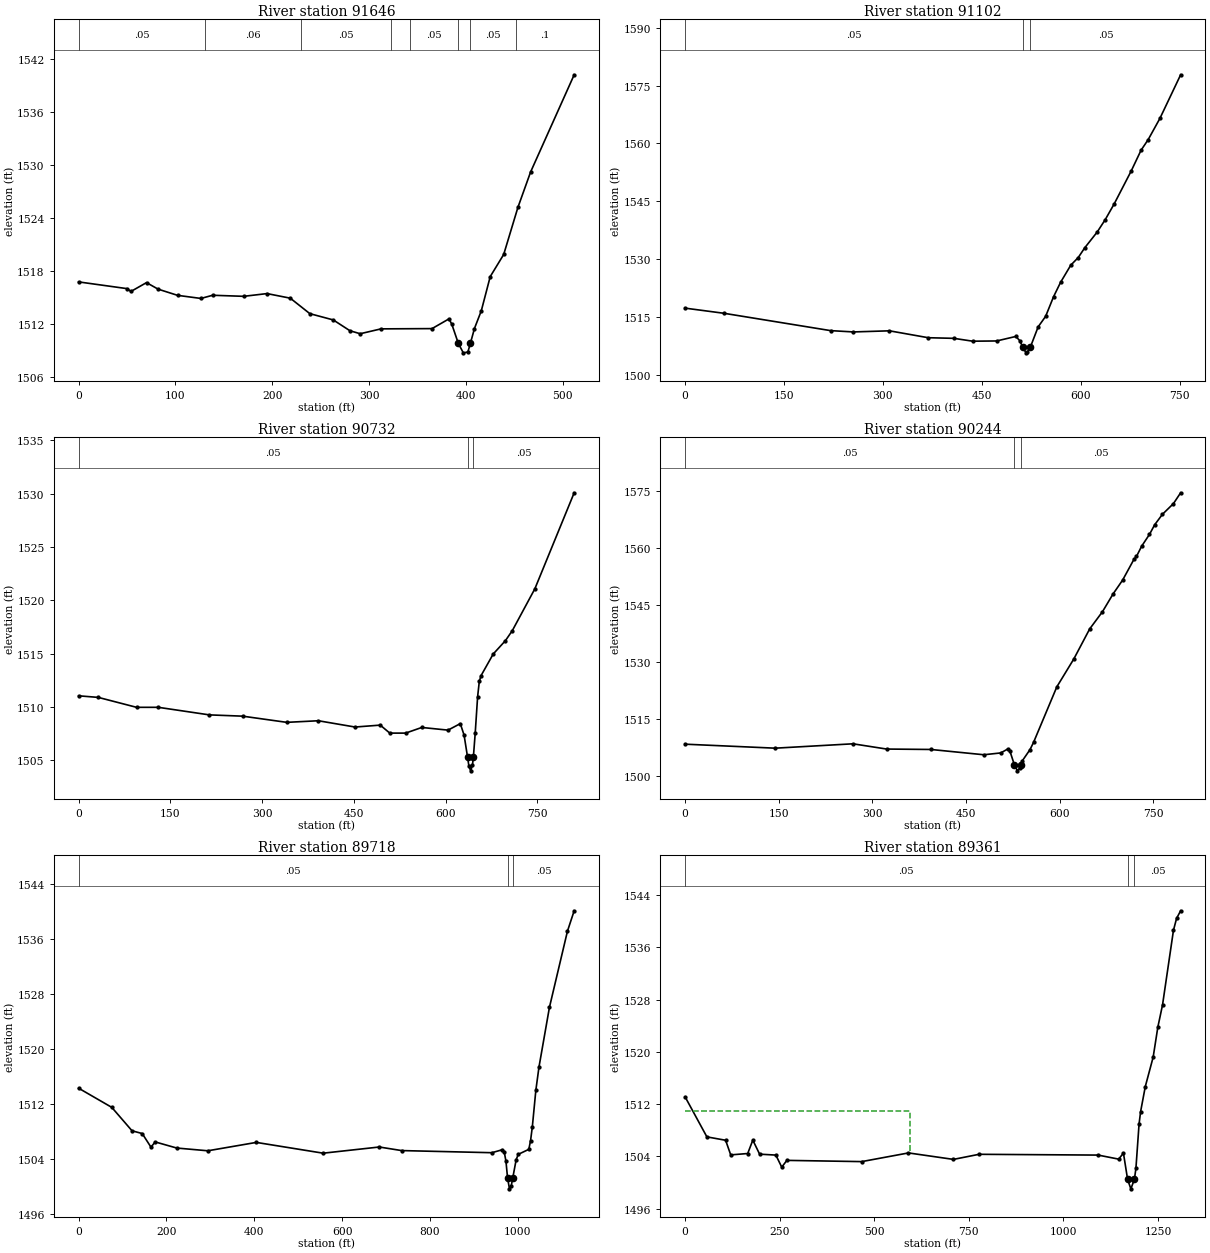
Type RM Length L Ch R = 1 ,91646   ,545.6,544.1,540.5
XS GIS Cut Line= 3
2149204.44899952687194.9345469212149180.07281556686933.962887363
2149054.17489893 686718.29932691
#Sta/Elev= 30
       0 1516.78      50 1516.02      54  1515.7    70.1  1516.7    82.1 1515.96
   102.2 1515.26   126.3 1514.91   138.4 1515.27   170.5 1515.15   194.6 1515.46
   218.6 1514.94   238.8 1513.19     263 1512.48   280.2 1511.26   290.8 1510.92
   312.3 1511.47     365  1511.5   382.5  1512.6   385.4    1512  392.191509.818
   397.3 1508.76     402 1508.85  404.581509.821   408.8 1511.51   415.9 1513.52
   425.1 1517.38     439 1519.88   453.7 1525.21   466.8 1529.21   511.8  1540.2
#Mann= 8 ,-1,0
       0     .05       0     130     .06       0     230     .05       0
  322.11     .06       0  342.11     .05       0  392.19    .045       0
  404.58     .05       0  452.11      .1       0
Bank Sta=392.19,404.58
XS Rating Curve= 0 ,0
Exp/Cntr=0.3,0.1

Type RM Length L Ch R = 1 ,91102   ,364.3,369.1,366.4
XS GIS Cut Line= 3
2149759.26860929686928.084137691 2149644.1542895686572.706506948
2149338.68655077686349.758163505
#Sta/Elev= 30
       0 1517.29    58.8 1515.96   220.7 1511.46   255.3 1511.12     310 1511.41
   368.9 1509.62   407.6 1509.46   436.2 1508.72   472.6 1508.78   501.7 1509.95
   507.8 1508.83  512.08 1507.19   517.1  1505.7   519.2 1505.89  523.76 1507.19
   535.6 1512.45   546.9 1515.16   558.9 1520.24   569.5 1523.96     585 1528.42
   596.4 1530.42   606.3 1532.95   625.1 1537.02   637.4 1540.26   650.9 1544.32
   676.7 1552.85   691.6 1558.22   702.4 1560.97   720.2 1566.47   751.7  1577.8
#Mann= 3 ,-1,0
       0     .05       0  512.08    .045       0  523.76     .05       0
Bank Sta=512.08,523.76
XS Rating Curve= 0 ,0
Exp/Cntr=0.3,0.1

Type RM Length L Ch R = 1 ,90732   ,491.6,488.5,482.8
XS GIS Cut Line= 4
2149993.48372462686777.8891566072149854.49886608 686317.60776514
2149740.45258348686241.8861101532149613.51588295686097.095134242
#Sta/Elev= 30
       0 1511.04    32.2 1510.89    94.7 1509.96   130.3 1509.96   213.8 1509.25
   268.2 1509.13   340.3 1508.55     392  1508.7     452 1508.11   493.2 1508.29
   508.8 1507.54   534.7 1507.54   561.1 1508.07     604 1507.82   624.1 1508.43
   630.3 1507.35  635.941505.296   638.2 1504.43   641.1    1504   643.9 1504.52
  645.481505.292   648.5 1507.55   652.4 1510.95   655.2  1512.4   658.1 1512.94
   677.9 1514.96   697.8 1516.21   709.1 1517.15     746 1521.08   810.3 1530.09
#Mann= 3 ,-1,0
       0     .05       0  635.94    .045       0  645.48     .05       0
Bank Sta=635.94,645.48
XS Rating Curve= 0 ,0
Exp/Cntr=0.3,0.1

Type RM Length L Ch R = 1 ,90244   ,523.8,526.5,523
XS GIS Cut Line= 4
2150386.25580168686246.908908748 2150042.4996106685864.647478119
2149999.08098604685863.7218071362149772.20492968685797.952640245
#Sta/Elev= 30
       0 1508.39   144.3 1507.34   268.9 1508.49   322.8 1507.11   393.6    1507
   478.5 1505.61   505.6 1506.09   516.4 1507.09   520.4 1506.51  527.251503.034
   532.4 1501.38   536.4 1502.15  538.231503.038   540.4 1504.09   552.4 1506.95
   558.1 1508.86   595.4 1523.47   622.6  1530.8     648  1538.7   668.5 1543.23
   685.5 1547.91   700.8 1551.55   718.8 1556.97     723 1557.78   731.3 1560.47
   743.8 1563.57   752.1 1566.09   764.6 1568.86   782.2 1571.67   793.7 1574.51
#Mann= 3 ,-1,0
       0     .05       0  527.25    .045       0  538.23     .05       0
Bank Sta=527.25,538.23
XS Rating Curve= 0 ,0
Exp/Cntr=0.3,0.1

Type RM Length L Ch R = 1 ,89718   ,352.5,356.6,355.7
XS GIS Cut Line= 3
2150837.53804911 685912.495447252150035.75469907685381.857964324
2149868.84982885685382.218148913
#Sta/Elev= 30
       0  1514.3    75.5 1511.51   121.6  1508.1   144.8  1507.7   164.7 1505.72
   174.3 1506.48   223.4 1505.59   294.2 1505.19   404.6 1506.41   556.8 1504.84
   684.6 1505.74   735.5 1505.22     941 1504.91   965.1 1505.35   969.1 1505.05
   973.1 1503.65  976.761501.195   981.1 1499.65   985.1 1500.09  988.451501.197
   996.3 1503.89  1001.1 1504.67  1025.1  1505.4  1029.1 1506.67  1033.1 1508.66
  1041.1 1513.98  1048.2 1517.36  1072.1 1526.08  1113.1 1537.16  1128.4 1540.13
#Mann= 3 ,-1,0
       0     .05       0  976.76    .045       0  988.45     .05       0
Bank Sta=976.76,988.45
XS Rating Curve= 0 ,0
Exp/Cntr=0.3,0.1

Type RM Length L Ch R = 1 ,89361   ,357.4,361.7,361.6
XS GIS Cut Line= 3
2151135.42716596685584.9728386692150111.02508738685058.917148913
2149957.90199379 685018.87269286
#Sta/Elev= 30
       0 1513.11    57.6 1506.98   107.1 1506.46   120.6 1504.22   165.5 1504.43
     179 1506.48     197 1504.33   239.9 1504.19   255.5 1502.34     269 1503.38
   466.8 1503.19   590.5 1504.52   709.3 1503.53   777.1 1504.31  1091.8 1504.19
  1146.1 1503.57  1158.7 1504.49 1169.741500.455  1178.3 1499.02 1187.621500.458
  1191.7 1502.16    1200 1508.95  1204.1 1510.85  1216.5 1514.69  1237.3  1519.2
  1249.6 1523.78    1262 1527.18    1291 1538.64  1299.2 1540.45  1309.9 1541.61
#Mann= 3 ,-1,0
       0     .05       0 1169.74    .045       0 1187.62     .05       0
#XS Ineff= 2 , 0
          593.92 1510.88
Permanent Ineff=
       F       F
Bank Sta=1169.74,1187.62
XS Rating Curve= 0 ,0
Exp/Cntr=0.3,0.1

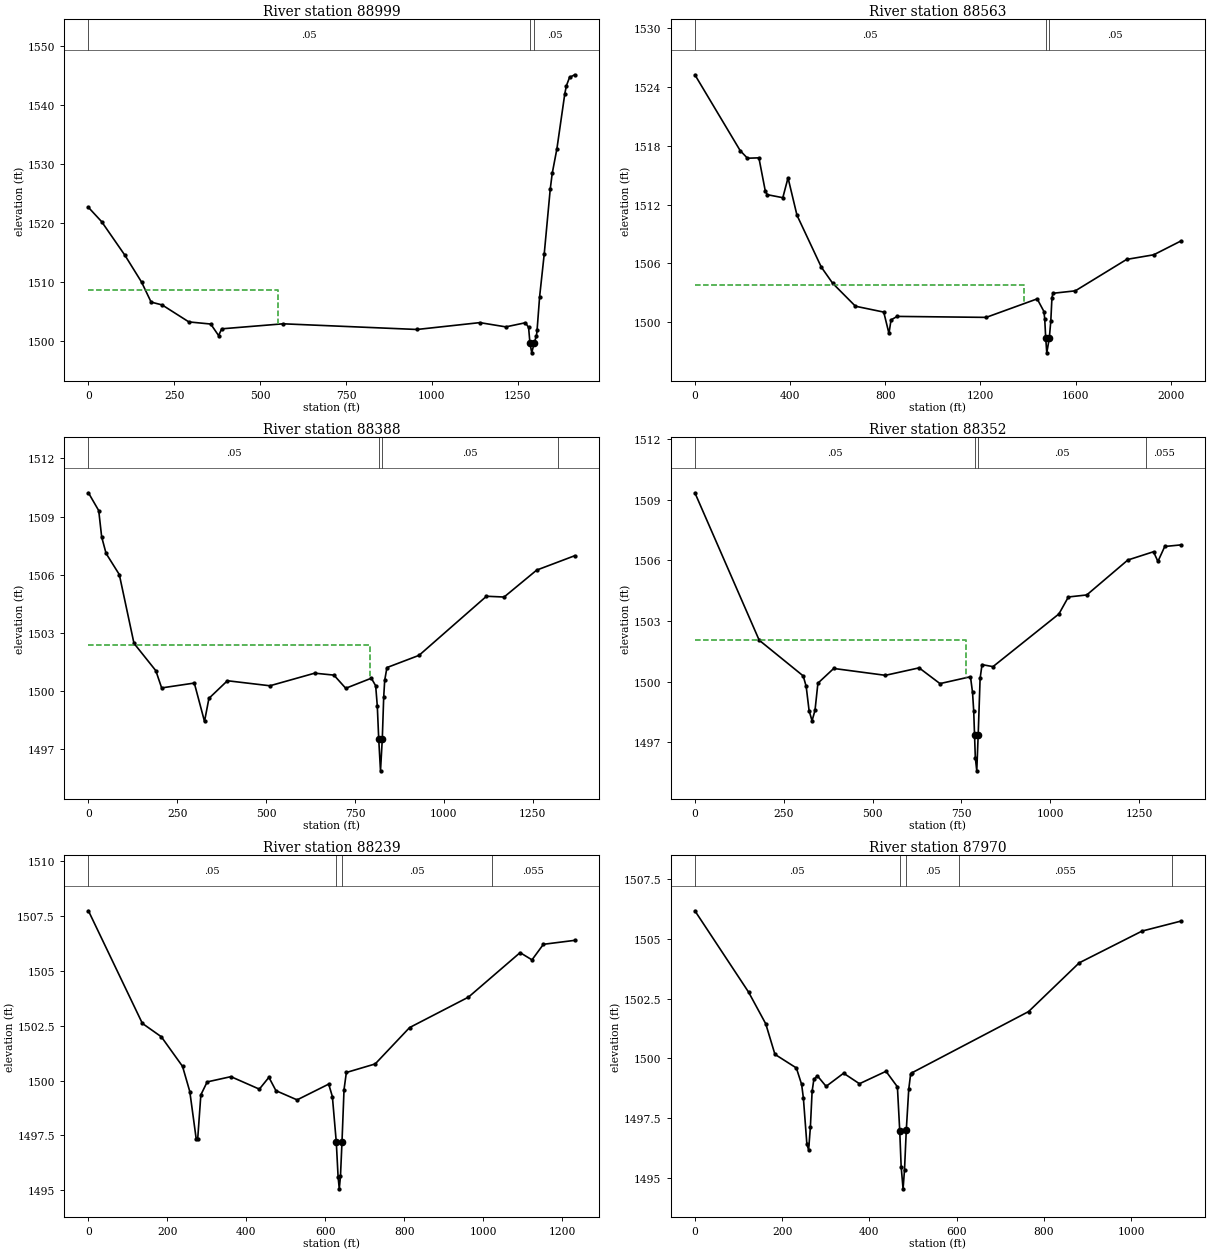
Type RM Length L Ch R = 1 ,88999   ,433.4,436.7,432.7
XS GIS Cut Line= 3
2151402.48037698685274.6257302742151184.23804709685261.661714966
2150139.12647533684677.502390053
#Sta/Elev= 30
       0 1522.65    38.4 1520.24   106.5 1514.53   154.8 1510.01   182.6 1506.63
   214.7 1506.15   292.5 1503.28   356.2 1502.92   379.1 1500.97   388.2 1502.11
     567 1502.96   956.8    1502  1139.8 1503.16  1215.5 1502.44  1272.7 1503.14
  1281.8 1502.34 1285.671499.758    1291 1498.05 1298.251499.758  1304.7 1500.93
  1306.6 1501.93  1313.9 1507.53  1327.2 1514.68  1344.8 1525.71  1350.6 1528.39
  1364.3 1532.57  1387.2 1541.84  1391.8  1543.2    1401 1544.62  1415.9 1545.07
#Mann= 3 ,-1,0
       0     .05       0 1285.67    .045       0 1298.25     .05       0
#XS Ineff= 2 , 0
          552.56 1508.62
Permanent Ineff=
       F       F
Bank Sta=1285.67,1298.25
XS Rating Curve= 0 ,0
Exp/Cntr=0.3,0.1

Type RM Length L Ch R = 1 ,88563   ,174.4,174.6,173.3
XS GIS Cut Line= 4
2151734.29377047685016.7204672032150435.39580072684443.833469262
2150333.56439732684376.0895100342149889.41943955684143.850530738
#Sta/Elev= 30
       0 1525.26   190.3 1517.52   220.9 1516.74     269 1516.78   295.5 1513.44
     304 1513.02   369.5 1512.71   391.4 1514.74     429 1510.92   531.3 1505.62
   579.4 1503.96   674.7 1501.63   793.6 1501.03   815.5 1498.85   824.2 1500.23
   849.8 1500.59  1223.9 1500.49  1438.3 1502.38  1466.7 1501.09    1470 1500.35
 1474.211498.371  1478.7 1496.87 1489.261498.371  1495.6 1500.13  1500.4 1502.51
  1504.6 1502.95  1598.5  1503.2  1814.3 1506.41    1928 1506.88  2043.1  1508.3
#Mann= 3 ,-1,0
       0     .05       0 1474.21    .045       0 1489.26     .05       0
#XS Ineff= 2 , 0
          1383.1 1503.75
Permanent Ineff=
       F       F
Bank Sta=1474.21,1489.26
XS Rating Curve= 0 ,0
Exp/Cntr=0.3,0.1

Type RM Length L Ch R = 1 ,88388   ,36.3,36.3,36.3
XS GIS Cut Line= 5
2151244.29344662684334.1511804972150897.98242858684423.896557009
2150828.16593082 684427.92443188 2150757.0068081684414.498182311
2149988.46946946684011.619146273
#Sta/Elev= 30
       0 1510.23      29 1509.31    37.3 1507.95    49.7  1507.1    86.9 1506.01
   128.2 1502.46   189.6 1501.05     206 1500.16   297.9 1500.41   326.6 1498.43
     339 1499.62     391 1500.53   510.6 1500.27   636.5 1500.92   690.7 1500.82
   723.9 1500.14   795.9 1500.66   808.1 1500.27   812.7 1499.22  816.711497.514
   821.7 1495.88   826.71497.513   830.7 1499.69   833.5 1500.55   839.8 1501.21
   930.1 1501.84  1119.8 1504.89  1169.4 1504.85  1261.1 1506.241367.831 1506.98
#Mann= 4 ,-1,0
       0     .05       0  816.71    .045       0   826.7     .05       0
  1320.1    .055       0
#XS Ineff= 2 , 0
          793.46 1502.39
Permanent Ineff=
       F       F
Bank Sta=816.71,826.7
XS Rating Curve= 0 ,0
Exp/Cntr(USF)=0,0
Exp/Cntr=0.3,0.1

Type RM Length L Ch R = 1 ,88352   ,113,113.1,112.2
XS GIS Cut Line= 5
2151235.24534233684288.4561574762150888.93432429684378.201533988
2150819.11782653684382.2294088592150747.95870381 684368.80315929
2149979.42136517683965.924123252
#Sta/Elev= 30
       0 1509.35   180.9 1502.05   304.8 1500.28   313.1 1499.76   321.3 1498.56
   329.6 1498.06   337.9 1498.57   346.1 1499.92   390.6 1500.65     536 1500.31
   630.8 1500.68   689.5  1499.9   775.3 1500.24   781.1 1499.46   784.4 1498.54
   786.71497.365   788.9 1496.24     793 1495.58     7971497.363   802.4 1500.16
   807.8 1500.84   838.6 1500.74  1024.1 1503.35  1050.7 1504.19  1102.4 1504.29
  1217.9 1506.02  1290.2 1506.43  1302.6 1505.95  1321.8 1506.691367.831 1506.77
#Mann= 4 ,-1,0
       0     .05       0   786.7    .045       0     797     .05       0
  1270.1    .055       0
#XS Ineff= 2 , 0
           762.7 1502.08
Permanent Ineff=
       F       F
Bank Sta=786.7,797
XS Rating Curve= 0 ,0
Exp/Cntr(USF)=0,0
Exp/Cntr=0.3,0.1

Type RM Length L Ch R = 1 ,88239   ,265.7,268.5,264.5
XS GIS Cut Line= 4
2151168.61018993684201.5685425382150713.47944847 684220.64736288
 2150518.8823071684124.253653115 2149989.2069353683947.518710748
#Sta/Elev= 30
       0 1507.75   136.6 1502.61   184.6    1502   238.3 1500.65   256.7  1499.5
   272.9 1497.34   276.7 1497.34   284.7 1499.35   300.7 1499.94   360.8 1500.18
   432.8 1499.61     457 1500.15   474.8 1499.54   528.4 1499.12   608.4 1499.84
   617.7 1499.27  627.611497.192   632.2  1495.6   635.2 1495.06   638.2 1495.64
  642.041497.196   647.2 1499.59   653.1 1500.37   726.1 1500.76   813.2 1502.42
   962.3 1503.81    1093 1505.84  1123.1 1505.51    1152 1506.22  1231.1  1506.4
#Mann= 4 ,-1,0
       0     .05       0  627.61    .045       0  642.04     .05       0
 1022.69    .055       0
Bank Sta=627.61,642.04
XS Rating Curve= 0 ,0
Exp/Cntr=0.3,0.1

Type RM Length L Ch R = 1 ,87970   ,524.8,535.1,530.8
XS GIS Cut Line= 5
2151106.22899558684026.6419113622150912.29427958 683961.99700603
2150691.83857679683945.4213892792150600.67268465 683907.29747075
2150010.58072829683915.585279126
#Sta/Elev= 30
       0 1506.18   122.9 1502.78   162.4 1501.45   183.5 1500.17   232.6  1499.6
   244.7 1498.91   248.7 1498.34   256.7 1496.41   260.7 1496.17   264.7 1497.11
   268.7 1498.62   272.7 1499.12   280.8 1499.27   300.8 1498.83   340.9 1499.38
   377.2 1498.94   438.1 1499.46   464.2 1498.81  469.54 1496.97   472.8 1495.47
   477.2 1494.54   480.5 1495.34  484.551496.994   490.2 1498.71   494.5 1499.34
   498.8 1499.41   764.8 1501.96   880.9    1504  1024.9 1505.331114.469 1505.75
#Mann= 5 ,-1,0
       0     .05       0  469.54    .045       0  484.55     .05       0
  604.32    .055       0 1094.32     .05       0
Bank Sta=469.54,484.55
XS Rating Curve= 0 ,0
Exp/Cntr(USF)=0,0
Exp/Cntr=0.3,0.1

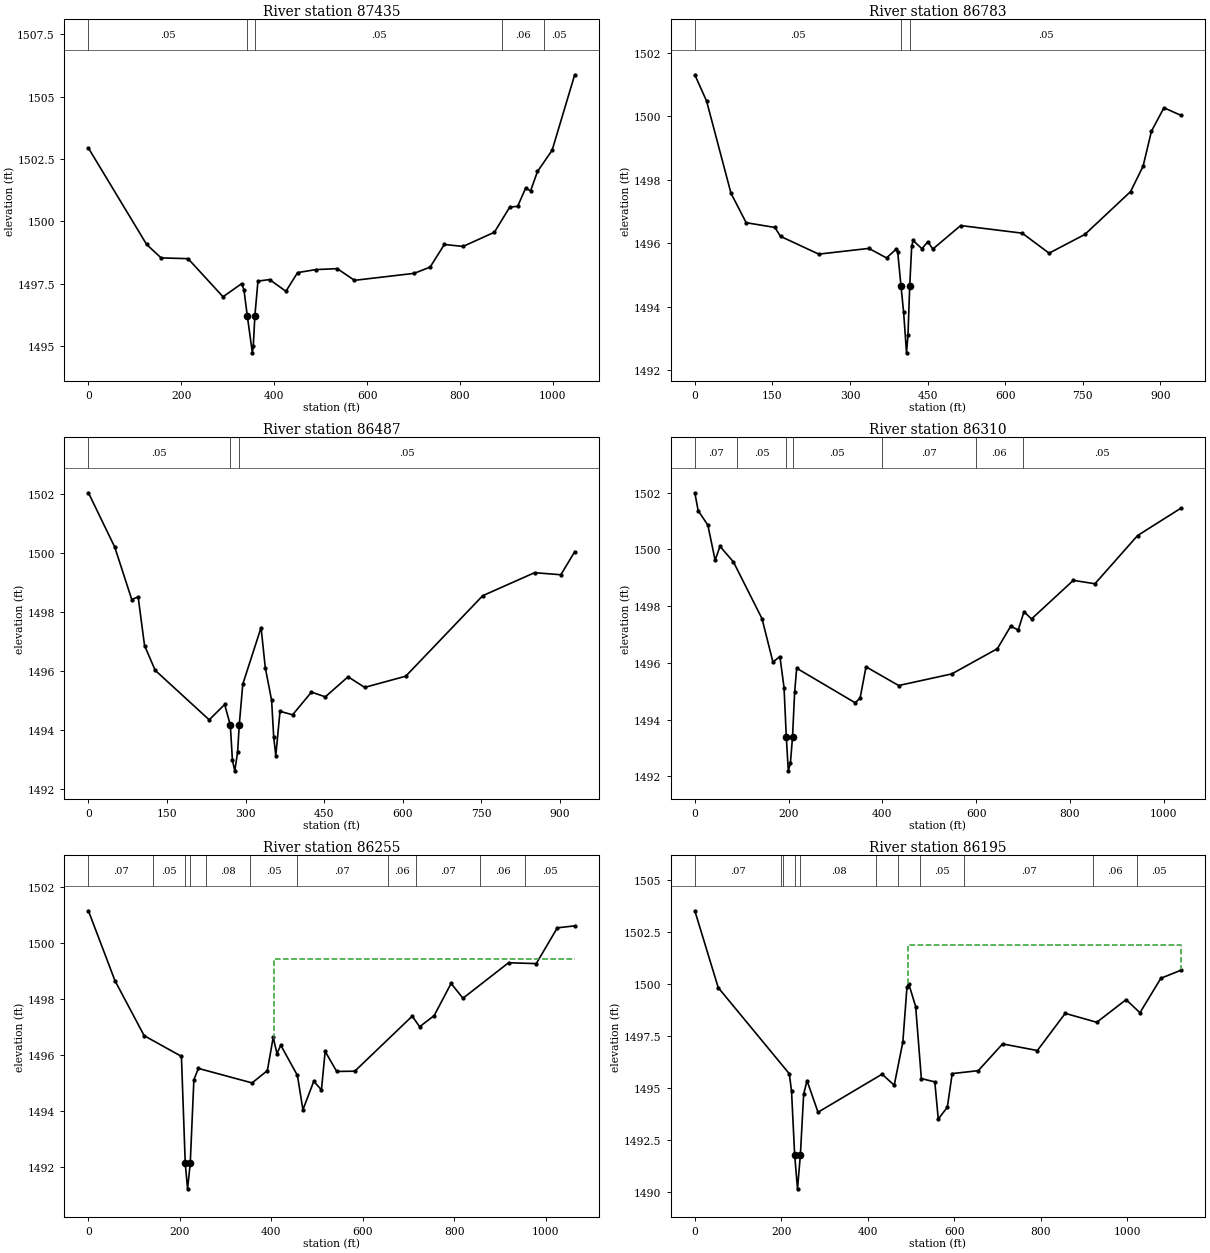
Type RM Length L Ch R = 1 ,87435   ,645.8,652.2,650.4
XS GIS Cut Line= 3
2151111.10450466683743.3609958612150967.28764185683589.509131371
2150300.45499346683084.868536719
#Sta/Elev= 30
       0 1502.94   125.3 1499.07   156.6 1498.53   214.5  1498.5   289.8 1496.97
   330.1  1497.5   334.9 1497.24  342.051496.203     353 1494.72     355 1495.01
  358.341496.203     365  1497.6   390.1 1497.66   425.2 1497.19   450.3 1497.94
   489.5 1498.06   535.7  1498.1   572.8 1497.63   701.1 1497.91   735.6 1498.16
   766.3 1499.07   806.4 1498.99     874 1499.56   907.1 1500.57   924.1  1500.6
   941.2 1501.33   951.9 1501.22   966.8    1502   998.3 1502.85  1046.9 1505.88
#Mann= 5 ,-1,0
       0     .05       0  342.05    .045       0  358.34     .05       0
   890.6     .06       0   980.6     .05       0
Bank Sta=342.05,358.34
XS Rating Curve= 0 ,0
Exp/Cntr=0.3,0.1

Type RM Length L Ch R = 1 ,86783   ,293.3,295.5,296
XS GIS Cut Line= 4
2151436.40546996683233.3015843862151347.72239074683187.415250669
2151048.56418952 682892.508922382150631.27210677682943.935101033
#Sta/Elev= 30
       0 1501.31    22.8 1500.48    69.9 1497.58    99.3 1496.65   154.9  1496.5
   165.7 1496.22   239.6 1495.66   336.6 1495.84   370.8 1495.54   389.6 1495.82
   392.4 1495.72  398.741494.647   403.8 1493.83   409.4 1492.55   412.2  1493.1
  415.571494.647   419.4 1495.91   422.1 1496.09   439.2 1495.83   450.6 1496.05
   460.3 1495.82   514.1 1496.56   633.2 1496.32   685.1 1495.69   754.3 1496.28
   842.7 1497.63   866.9 1498.43     883 1499.53   907.2 1500.27   940.4 1500.03
#Mann= 3 ,-1,0
       0     .05       0  398.74    .045       0  415.57     .05       0
Bank Sta=398.74,415.57
XS Rating Curve= 0 ,0
Exp/Cntr=0.3,0.1

Type RM Length L Ch R = 1 ,86487   ,179,176.9,173
XS GIS Cut Line= 4
2151577.61097218682902.6695543052151413.99149781682873.262419133
2151321.67863213682745.2623788372150717.74254039682738.012390584
#Sta/Elev= 30
       0 1502.04    50.2  1500.2    82.7 1498.42    94.9 1498.51   107.1 1496.86
   127.4 1496.02   230.5 1494.34     260 1494.86  270.791494.162   274.8 1492.97
   279.3 1492.61   284.7 1493.24   287.9 1494.18   294.6 1495.55   329.5 1497.47
   337.5 1496.11   349.6    1495   353.6 1493.75   357.6 1493.13   365.6 1494.63
   389.6 1494.51   425.6 1495.28   452.1 1495.12   495.5  1495.8   527.2 1495.44
   605.6 1495.82   752.5 1498.55   851.4 1499.33   901.6 1499.26     928 1500.04
#Mann= 3 ,-1,0
       0     .05       0  270.79    .045       0   287.9     .05       0
Bank Sta=270.79,287.9
XS Rating Curve= 0 ,0
Exp/Cntr=0.3,0.1

Type RM Length L Ch R = 1 ,86310   ,55.1,55.6,56
XS GIS Cut Line= 6
2151673.64027854682777.5358688382151600.36716815 682717.26037249
2151534.68713964682710.231171213 2151465.7846132682676.009083401
2151321.07947896682631.2549181712150681.10557859  682529.9460817
#Sta/Elev= 30
       0    1502     7.1 1501.37    27.8 1500.86    43.3 1499.62    53.7 1500.11
    82.4 1499.56   143.3 1497.56   166.6 1496.03   181.5 1496.22   190.3 1495.13
  195.121493.389   199.4 1492.19   203.9 1492.46  208.421493.388   212.9 1494.96
   217.3 1495.81   342.2 1494.59   352.6 1494.76   365.2 1495.86   434.8  1495.2
   548.2 1495.61   645.4  1496.5   673.7 1497.29   689.9 1497.16   702.1  1497.8
   718.3 1497.55   807.4 1498.91   853.5 1498.79   944.4 1500.49  1037.3 1501.46
#Mann= 7 ,-1,0
       0     .07       0      90     .05       0  195.12    .045       0
  208.42     .05       0  399.34     .07       0  599.34     .06       0
  699.34     .05       0
Bank Sta=195.12,208.42
XS Rating Curve= 0 ,0
Exp/Cntr=0.3,0.1

Type RM Length L Ch R = 1 ,86255   ,57.6,59.9,62.5
XS GIS Cut Line= 6
2151729.31763731682740.1205954822151617.77561258682669.793454748
2151562.79847332682664.9048313212151493.89594688682630.682743508
2151349.19081264682585.9285782792150709.21691227682484.619741808
#Sta/Elev= 30
       0 1501.16      58 1498.66   121.9 1496.69   203.4 1495.95  211.75 1492.12
   216.8 1491.21  222.661492.119   230.6 1495.11   240.4 1495.52   357.9    1495
   391.3 1495.44   404.1 1496.63   412.3 1496.05   420.6 1496.35     457 1495.27
   469.1 1494.04   492.8 1495.06   509.6 1494.75   517.7 1496.13   542.9 1495.41
   582.5 1495.42   708.1 1497.39   724.3 1497.01   756.1 1497.41   793.1 1498.56
   819.1 1498.03   918.7  1499.3   979.4 1499.27  1025.4 1500.55  1063.4 1500.62
#Mann= 11 ,-1,0
       0     .07       0  141.86     .05       0  211.75    .045       0
  222.66     .05       0  257.06     .08       0  353.99     .05       0
  455.46     .07       0  655.46     .06       0  715.46     .07       0
  855.46     .06       0  955.46     .05       0
#XS Ineff= 2 , 0
                          404.96         1499.45
Permanent Ineff=
       F       F
Bank Sta=211.75,222.66
XS Rating Curve= 0 ,0
Exp/Cntr=0.3,0.1

Type RM Length L Ch R = 1 ,86195   ,87.2,90.7,95.3
XS GIS Cut Line= 5
2151781.10197309 682730.077309652151599.13075466682635.814745537
 2151558.7211021682585.0569551082151343.07770396682533.524525407
2150713.56583027682470.192666013
#Sta/Elev= 30
       0 1503.54    54.1 1499.84   218.5 1495.69   223.6 1494.85   230.81491.784
   237.4 1490.15  244.041491.786   251.6 1494.71   259.4 1495.36   284.8 1493.84
   432.8 1495.67     461 1495.14   480.9 1497.22   490.4 1499.85   494.4 1500.03
   510.5 1498.93   523.7 1495.46   554.8  1495.3   562.8 1493.51   583.8 1494.08
     595  1495.7   655.2 1495.84   711.5 1497.13   791.9 1496.81   856.3  1498.6
   929.2 1498.17     997 1499.26  1029.1 1498.63  1077.4 1500.29  1124.2 1500.68
#Mann= 11 ,-1,0
       0     .07       0     200     .05       0  204.94     .08       0
   230.8    .045       0  244.04     .08       0  419.82     .05       0
  469.82     .07       0  521.53     .05       0  621.53     .07       0
  921.53     .06       0 1021.53     .05       0
#XS Ineff= 2 , 0
                          493.52         1501.89
Permanent Ineff=
       F       F
Bank Sta=230.8,244.04
XS Rating Curve= 0 ,0
Exp/Cntr=0.3,0.1

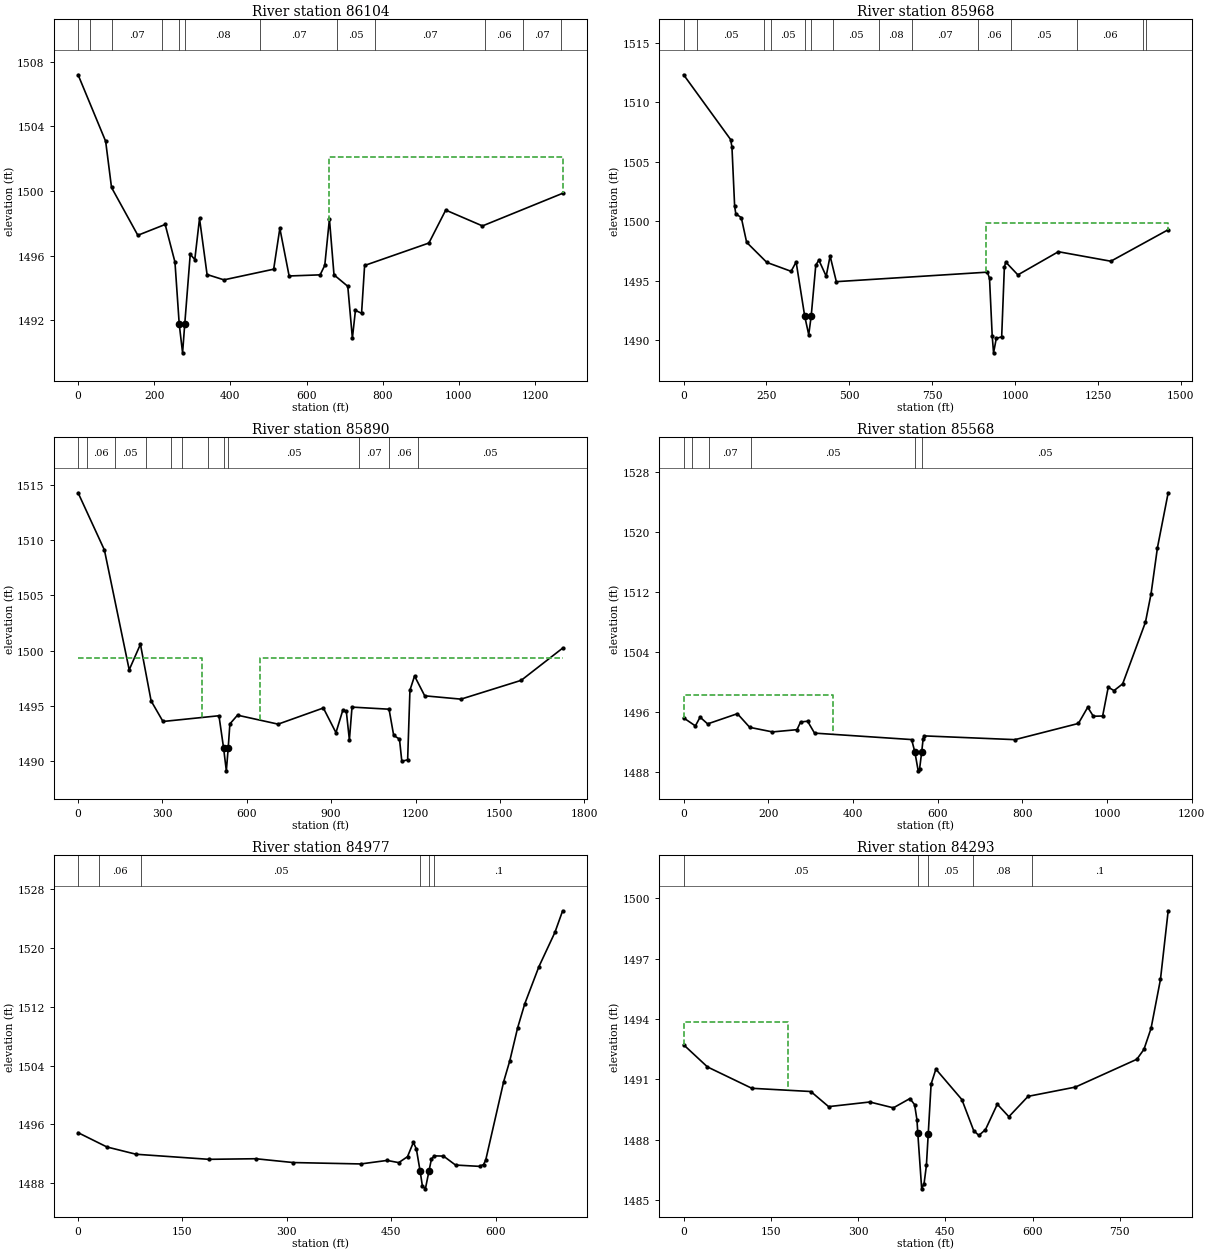
Type RM Length L Ch R = 1 ,86104   ,144.3,136,128
XS GIS Cut Line= 5
2151876.76759123682750.8837234392151668.98169942682624.125838473
2151664.07977614682549.2698310882151329.10982176682487.544462972
2150718.64873145682427.643519045
#Sta/Elev= 30
       0  1507.2    72.4 1503.08    87.8 1500.22   156.9 1497.26   228.7 1497.93
   254.4  1495.6   265.61491.757   274.4 1489.98  280.12 1491.77   294.5 1496.08
   306.5 1495.76   318.9  1498.3   338.7 1494.83     383  1494.5   513.6 1495.16
   529.8 1497.69   554.2 1494.74   635.6 1494.81   647.8  1495.4     660 1498.27
     672 1494.81   708.2  1494.1   720.3 1490.89   728.3 1492.61   744.4 1492.43
   752.4 1495.39   921.2 1496.78   965.4 1498.82  1061.9 1497.841272.417 1499.86
#Mann= 12 ,-1,0
       0     .07       0      30     .08       0      90     .07       0
     220     .08       0   265.6    .045       0  280.12     .08       0
  478.41     .07       0  679.02     .05       0  779.02     .07       0
 1069.02     .06       0 1169.02     .07       0 1269.02     .06       0
#XS Ineff= 2 , 0
                          659.38          1502.1
Permanent Ineff=
       F       F
Bank Sta=265.6,280.12
XS Rating Curve= 0 ,0
Exp/Cntr(USF)=0,0
Exp/Cntr=0.3,0.1

Type RM Length L Ch R = 1 ,85968   ,74.5,78.4,79.3
XS GIS Cut Line= 6
2151922.37600274682874.0162171862151944.85238723682682.556525107
2151842.08335936682596.2043495342151770.03927994682554.055883611
2151612.11006137682492.0022061372150745.75537407682330.088489751
#Sta/Elev= 30
       0 1512.32   141.8 1506.87   145.8 1506.24   153.9 1501.26   157.4 1500.62
     174  1500.3   190.1 1498.22     251 1496.53   324.3 1495.78   339.4 1496.57
  365.38 1491.99   377.4 1490.45   384.8    1492   398.7  1496.3     408 1496.72
   430.1 1495.37   441.9 1497.07   460.7 1494.91   916.4 1495.71   922.8 1495.19
   930.9 1490.35     935 1488.92   943.2 1490.13   959.5 1490.27   967.6 1496.12
   971.7 1496.56  1008.4 1495.48  1130.5 1497.43  1288.8 1496.63  1461.8 1499.28
#Mann= 14 ,-1,0
       0     .06       0      40     .05       0  242.77     .08       0
  262.77     .05       0  365.38    .045       0   384.8     .07       0
  450.47     .05       0  590.35     .08       0  690.35     .07       0
  886.81     .06       0  986.81     .05       0 1185.29     .06       0
 1385.29     .07       0 1395.29     .05       0
#XS Ineff= 2 , 0
                          911.32         1499.85
Permanent Ineff=
       F       F
Bank Sta=365.38,384.8
XS Rating Curve= 0 ,0
Exp/Cntr=0.3,0.1

Type RM Length L Ch R = 1 ,85890   ,316.5,321.9,322.9
XS GIS Cut Line= 6
2151948.97268997682954.7740211772152046.69641218682714.140310828
2151958.92835083682613.9070238962151856.15932296682527.554848323
2151626.18602498682423.3527049262150709.09005772682206.555563289
#Sta/Elev= 30
       0 1514.28    93.6 1509.11   181.8 1498.28   221.7 1500.59   259.7 1495.47
   301.9 1493.61     501 1494.13   517.5  1491.2   527.2 1489.15  533.74 1491.18
   539.8 1493.39   566.9 1494.18   711.3 1493.37   872.2 1494.83     917  1492.6
   941.5 1494.64   953.8 1494.53   964.8 1491.94   974.1 1494.91  1105.8 1494.72
  1122.3 1492.35  1142.9 1492.02  1151.2 1490.01  1171.9 1490.15  1180.1 1496.44
  1196.5 1497.72  1232.6 1495.93  1361.6 1495.63  1575.8 1497.33  1723.1 1500.24
#Mann= 12 ,-1,0
       0     .05       0      30     .06       0     130     .05       0
     240     .07       0  329.72     .05       0  369.72     .07       0
  462.95     .05       0   517.5    .045       0  533.74     .05       0
 1000.52     .07       0 1106.99     .06       0 1206.99     .05       0
#XS Ineff= 2 , 0
           439.1 1499.32     648         1499.36
Permanent Ineff=
       F       F
Bank Sta=517.5,533.74
XS Rating Curve= 0 ,0
Exp/Cntr=0.3,0.1

Type RM Length L Ch R = 1 ,85568   ,588.5,590.7,590.6
XS GIS Cut Line= 4
2152304.90517859682888.0150545982152205.96559948682516.100355529
2151959.11106427682114.384495854 2151839.5706756681852.289037335
#Sta/Elev= 30
       0 1495.19    27.8 1494.12    38.9 1495.29    56.7 1494.39     127 1495.75
   156.1 1493.93   209.9 1493.32   267.8 1493.62   276.1 1494.64   292.7 1494.75
   309.2 1493.16   538.5  1492.3  546.12 1490.64     554 1488.13   557.3 1488.39
  562.251490.637   565.7 1492.42   568.6 1492.79   782.6 1492.29   932.4 1494.45
   954.4 1496.61   967.6 1495.41   989.6 1495.44  1002.8 1499.28  1016.5 1498.83
  1036.9 1499.73  1090.7 1507.95  1103.9 1511.72  1119.1 1517.91  1144.4 1525.21
#Mann= 6 ,-1,0
       0     .06       0      20     .05       0      60     .07       0
     160     .05       0  546.12    .045       0  562.25     .05       0
#XS Ineff= 2 , 0
          352.23 1498.23
Permanent Ineff=
       F       F
Bank Sta=546.12,562.25
XS Rating Curve= 0 ,0
Exp/Cntr=0.3,0.1

Type RM Length L Ch R = 1 ,84977   ,675.4,684.4,682.6
XS GIS Cut Line= 3
2152800.02925067682624.7961010332152655.81164338682165.091726022
2152573.93841532681966.931529473
#Sta/Elev= 30
       0 1494.88    41.5 1492.93    83.4 1491.94   187.9 1491.25   255.3 1491.33
   309.1 1490.81   406.2 1490.62     444  1491.1   460.7  1490.8   473.3 1491.61
   481.7 1493.55     486 1492.67   491.51489.597   494.7 1487.61     499 1487.23
  504.031489.598   507.7  1491.3     512 1491.72     525 1491.69   542.3 1490.47
   576.9 1490.29   582.5 1490.54   585.6 1491.12   611.5 1501.84   620.2 1504.65
   631.5 1509.15   641.8 1512.44   662.1 1517.49   685.1 1522.16   696.2  1525.1
#Mann= 6 ,-1,0
       0     .05       0      30     .06       0      90     .05       0
   491.5    .045       0  504.03     .05       0   511.8      .1       0
Bank Sta=491.5,504.03
XS Rating Curve= 0 ,0
Exp/Cntr=0.3,0.1

Type RM Length L Ch R = 1 ,84293   ,429.8,431.2,427.5
XS GIS Cut Line= 3
       2153148.6      682536.8342153221.25557099682104.566001914
      2153150.93      681716.083
#Sta/Elev= 30
       0 1492.72      41 1491.62   117.3 1490.56   218.7  1490.4   249.3 1489.65
   320.1 1489.88   360.6 1489.59     389 1490.05   397.1 1489.75   401.2 1488.99
  402.581488.338   409.3 1485.57   413.4 1485.83   417.4 1486.73   420.6 1488.31
   425.5 1490.77   433.7 1491.51   478.4    1490   498.7 1488.46   507.6 1488.22
     519 1488.51   539.3 1489.77   559.2 1489.15   592.2 1490.16   673.5 1490.62
   779.2    1492   791.4 1492.49   803.6 1493.53   819.8 1495.96   833.1 1499.37
#Mann= 5 ,-1,0
       0     .05       0  402.58    .045       0   420.6     .05       0
  498.33     .08       0  598.33      .1       0
#XS Ineff= 2 , 0
          180.28 1493.83
Permanent Ineff=
       F       F
Bank Sta=402.58,420.6
XS Rating Curve= 0 ,0
Exp/Cntr=0.3,0.1

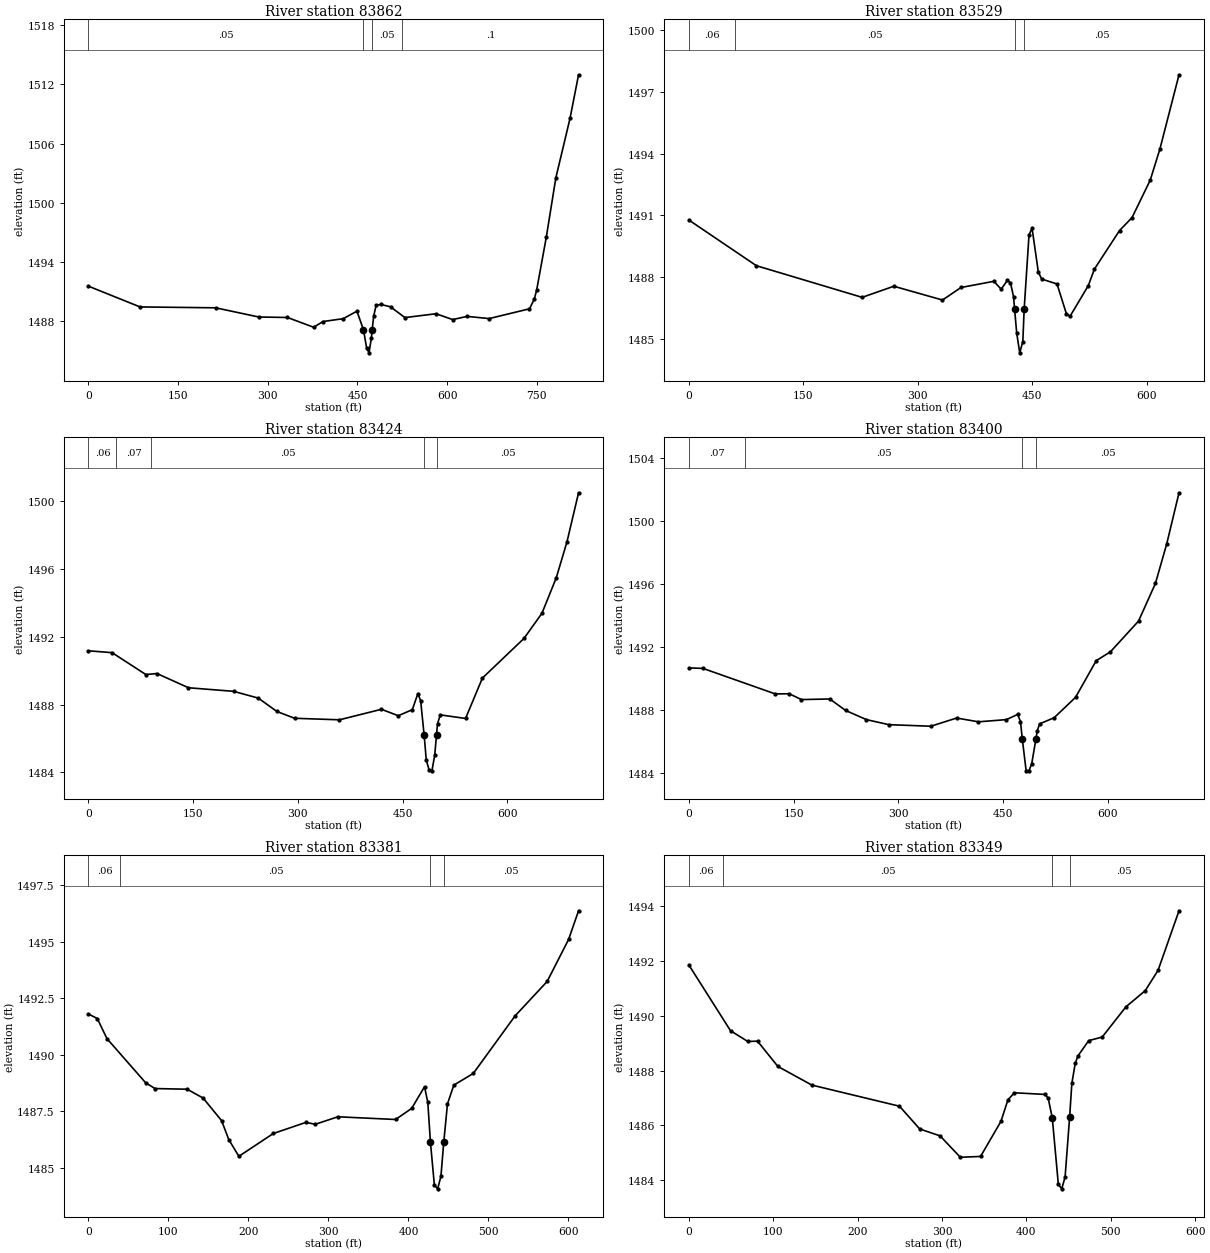
Type RM Length L Ch R = 1 ,83862   ,328.3,332.1,330
XS GIS Cut Line= 4
2153729.37230218682524.1347549942153609.16129066 682351.28812403
2153627.56901842682067.5499246842153607.64950815681743.191717795
#Sta/Elev= 30
       0 1491.57    86.2 1489.47   212.7 1489.38   284.8 1488.45   332.9  1488.4
   376.7 1487.41   392.3 1487.99   426.2 1488.28   449.1 1489.04     460 1487.15
   465.2 1485.34   469.2 1484.82   473.2 1486.28   474.5 1487.15   477.2 1488.58
   481.2 1489.63   489.2 1489.72   505.3 1489.48   529.3 1488.39   581.4 1488.78
   609.1 1488.19   633.5 1488.51   670.2 1488.29   737.7 1489.28   745.7 1490.25
   749.7 1491.17   765.8 1496.52   781.8 1502.54   805.5 1508.56   819.8 1512.98
#Mann= 4 ,-1,0
       0     .05       0     460    .045       0   474.5     .05       0
  524.87      .1       0
Bank Sta=460,474.5
XS Rating Curve= 0 ,0
Exp/Cntr=0.3,0.1

Type RM Length L Ch R = 1 ,83529   ,106.8,105.6,103.9
XS GIS Cut Line= 3
2153831.13383961 682497.324710232153901.54181431682053.819865574
 2153940.0336852681864.481473663
#Sta/Elev= 30
       0 1490.77    88.4 1488.55     227 1487.01   268.5 1487.55   332.3 1486.88
   356.6 1487.49   399.5 1487.79   409.2 1487.41   417.3 1487.83   421.4 1487.72
   425.4 1487.04   426.81486.438   429.5 1485.29   433.5 1484.31   437.6 1484.86
  439.32 1486.43   445.7 1490.05   449.7 1490.37   457.9 1488.24   462.3  1487.9
   482.4 1487.66   494.6 1486.22   499.3 1486.08   523.4 1487.58   531.3 1488.38
   564.3 1490.26   580.7 1490.89   604.5 1492.71   617.1 1494.21642.2703 1497.84
#Mann= 4 ,-1,0
       0     .06       0      60     .05       0   426.8    .045       0
  439.32     .05       0
Bank Sta=426.8,439.32
XS Rating Curve= 0 ,0
Exp/Cntr(USF)=0,0
Exp/Cntr=0.3,0.1

Type RM Length L Ch R = 1 ,83424   ,23.4,23.5,24
XS GIS Cut Line= 5
2153857.12136655682509.1897456022153984.82726443682320.924426749
2154004.07510065682077.2470058482153995.66439321681988.005779822
2153976.60040625681848.663230513
#Sta/Elev= 30
       0 1491.17    33.8 1491.06    82.2 1489.77    98.1 1489.83   143.3 1488.99
   207.9 1488.78   243.3 1488.38     270 1487.59   295.4 1487.19   359.6  1487.1
   419.8 1487.72   443.9 1487.34     464  1487.7     472 1488.65     476 1488.21
  480.921486.204     484 1484.73   488.1 1484.13   492.1 1484.09   496.1 1485.01
  498.661486.202   500.1 1486.87   504.1 1487.39   540.3 1487.18   564.4 1489.56
     624  1491.9   649.7 1493.38   670.2 1495.47   685.5 1497.58   702.2 1500.49
#Mann= 5 ,-1,0
       0     .06       0      40     .07       0      90     .05       0
  480.92    .045       0  498.66     .05       0
Bank Sta=480.92,498.66
XS Rating Curve= 0 ,0
Exp/Cntr=0.3,0.1

Type RM Length L Ch R = 1 ,83400   ,20.8,19.3,17.3
XS GIS Cut Line= 5
2153879.37596917682500.2181545432154007.08186706 682311.95283569
2154026.32970328682068.2754147882154017.91899583681979.034188763
2153998.85500888681839.691639453
#Sta/Elev= 30
       0 1490.67      20 1490.64   123.7 1489.02   143.8 1489.03   161.2 1488.66
   201.8  1488.7   224.5 1487.97   254.3 1487.39   286.4 1487.07   346.6 1486.97
   383.6 1487.49   414.8 1487.25     455 1487.39     471 1487.72     475 1487.27
  477.631486.168   483.1 1484.16   487.1 1484.14   491.1 1484.58  497.211486.169
   499.1 1486.69   502.5 1487.12   523.3 1487.51   553.9  1488.8   583.6 1491.13
   603.9 1491.69   644.2 1493.64   668.4 1496.03   684.6 1498.54   702.2 1501.78
#Mann= 4 ,-1,0
       0     .07       0      80     .05       0  477.63    .045       0
  497.21     .05       0
Bank Sta=477.63,497.21
XS Rating Curve= 0 ,0
Exp/Cntr=0.3,0.1

Type RM Length L Ch R = 1 ,83381   ,29.6,32.1,34.8
XS GIS Cut Line= 4
  2154015.617057 682476.174954312154044.63377895682059.951483646
2154036.01178333682022.9868612272154020.45317732681866.268828631
#Sta/Elev= 30
       0  1491.8      11  1491.6    23.1 1490.71    71.6 1488.75    83.2  1488.5
   123.3 1488.47   143.3 1488.08   166.4 1487.08   175.4 1486.24     188  1485.5
   231.1 1486.51   271.7    1487   283.7 1486.92   311.8 1487.25   383.9 1487.13
     404 1487.62   420.1 1488.58   424.2 1487.89  427.49 1486.13   432.4 1484.23
   436.5 1484.06   440.6 1484.61  444.211486.147   448.8 1487.82   456.7 1488.65
   481.1 1489.17   533.4 1491.72   573.4 1493.24   600.2  1495.1 612.679 1496.37
#Mann= 4 ,-1,0
       0     .06       0      40     .05       0  427.49    .045       0
  444.21     .05       0
Bank Sta=427.49,444.21
XS Rating Curve= 0 ,0
Exp/Cntr(USF)=0,0
Exp/Cntr=0.3,0.1

Type RM Length L Ch R = 1 ,83349   ,28.1,27,27.4
XS GIS Cut Line= 2
2154048.08096417682478.4030591192154079.47610596681898.306462005
#Sta/Elev= 30
       0 1491.84    49.3 1489.45    69.7 1489.06    81.3 1489.07   105.4 1488.15
   145.7 1487.47   249.6  1486.7   273.6 1485.87   297.7 1485.62   321.7 1484.84
   345.7 1484.87   369.9 1486.15   378.1 1486.93   385.8 1487.19   421.8 1487.13
   425.8    1487   430.7 1486.28   437.9 1483.85   441.9 1483.69   445.9 1484.12
  451.27  1486.3   453.9 1487.53   457.9 1488.26   461.1 1488.53   473.9 1489.09
   489.9 1489.22     518 1490.32   540.9 1490.91   556.1 1491.65580.9456 1493.82
#Mann= 4 ,-1,0
       0     .06       0      40     .05       0   430.7    .045       0
  451.27     .05       0
Bank Sta=430.7,451.27
XS Rating Curve= 0 ,0
Exp/Cntr(USF)=0,0
Exp/Cntr=0.3,0.1