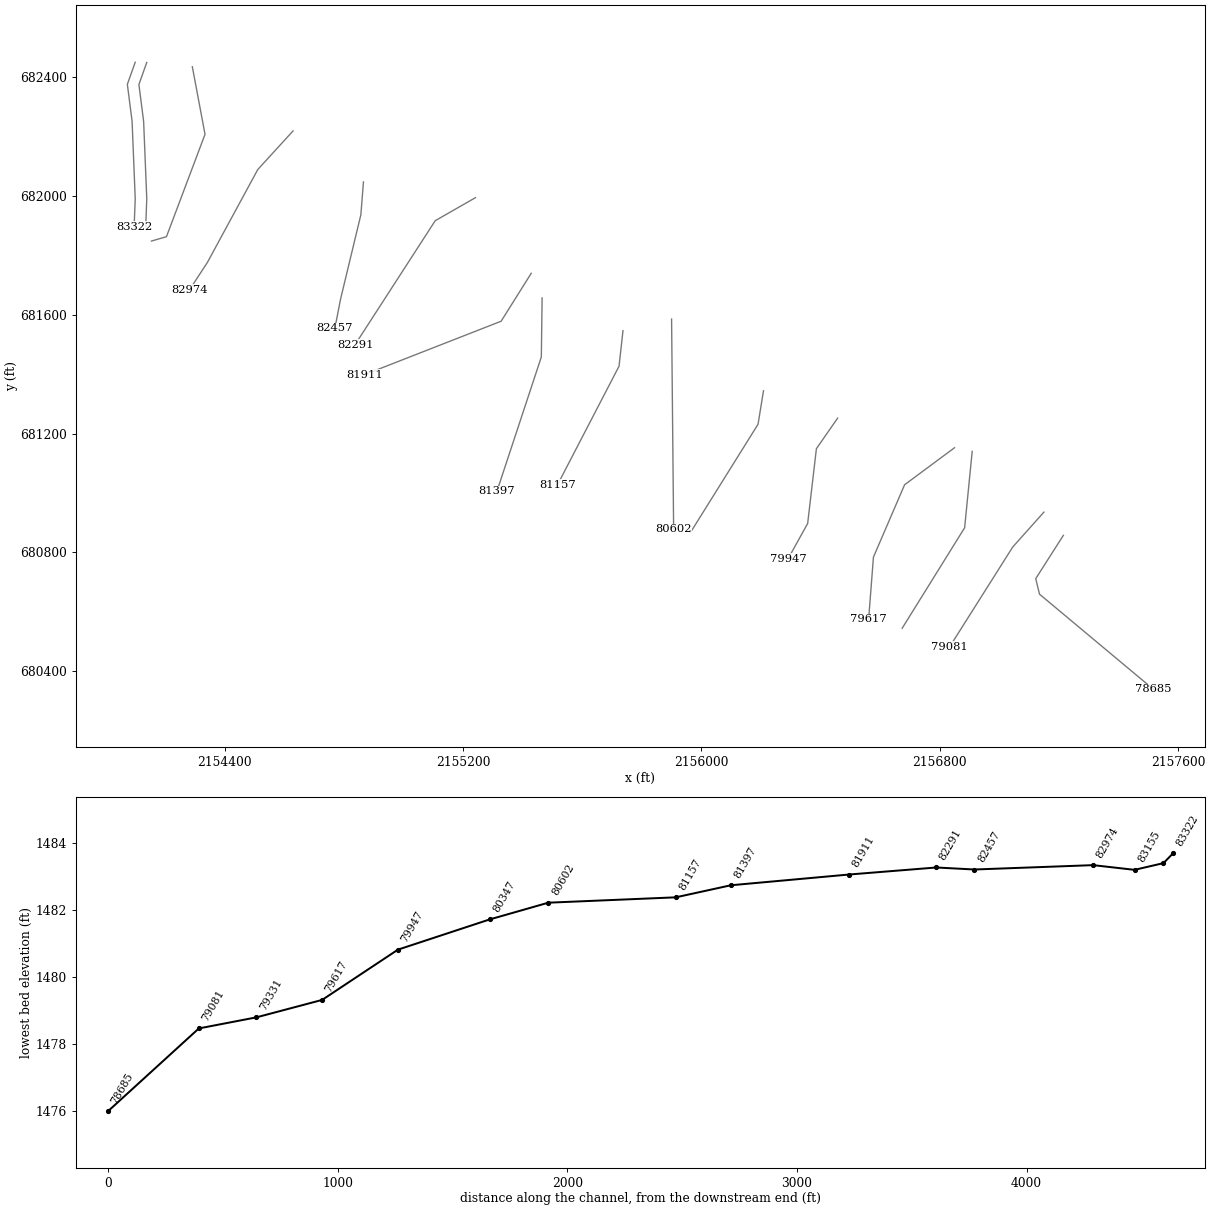
HEC-RAS study FRENCHCK.prj: FRENCHCK

--- FRENCHCK.g01 (geometry) --- (continued)

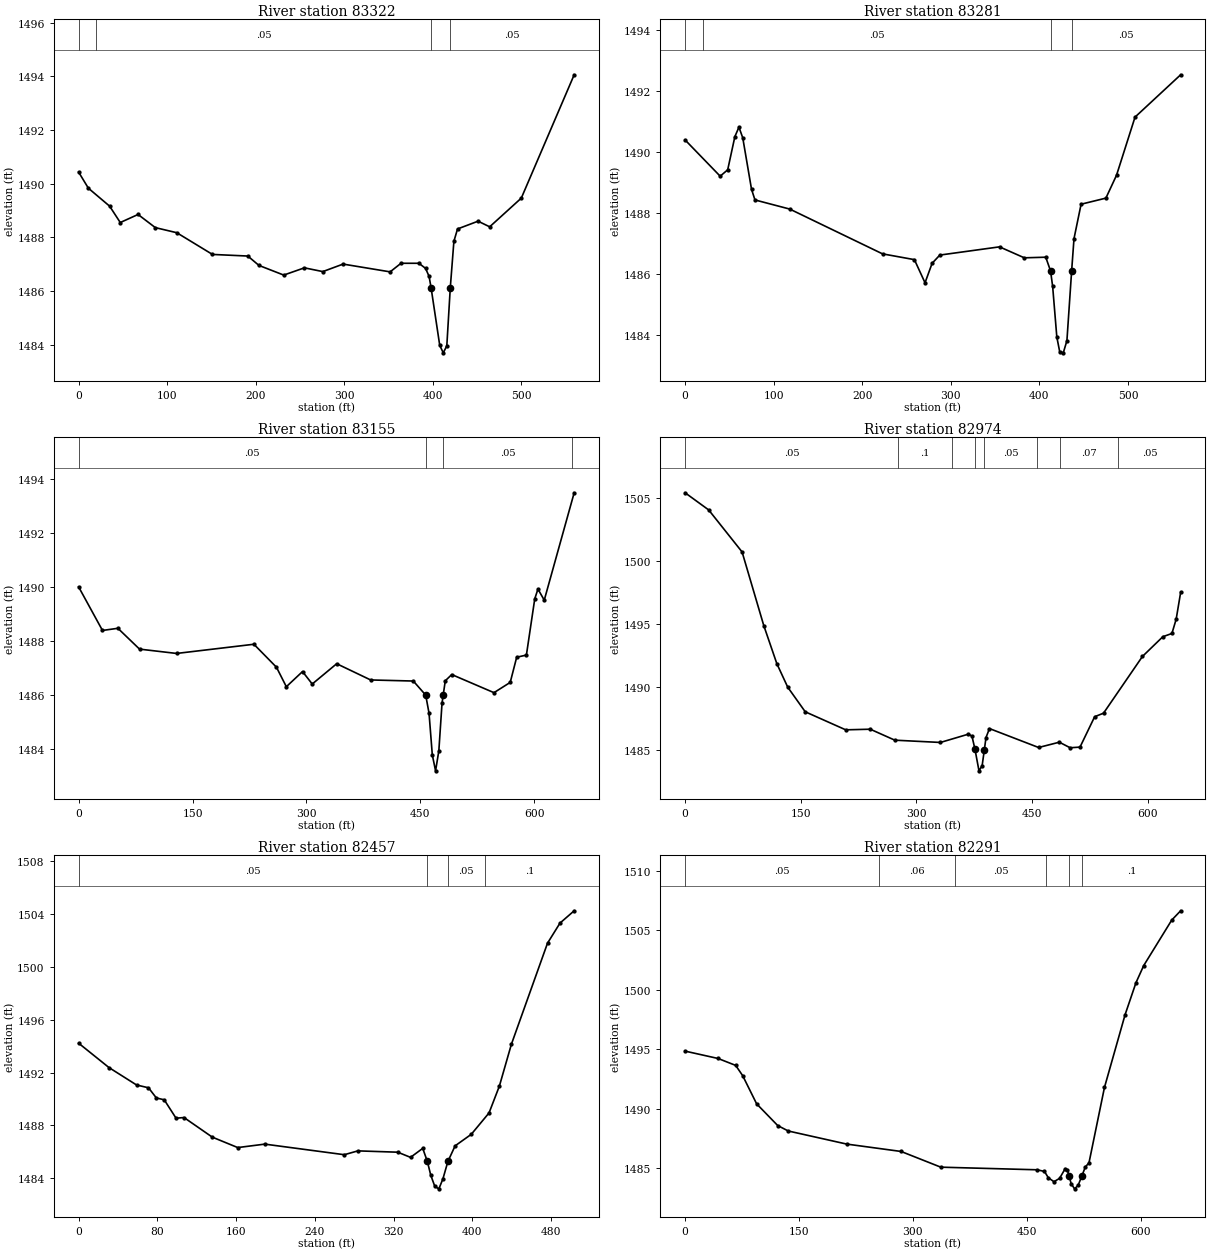
Type RM Length L Ch R = 1 ,83322   ,42.3,41.4,43.2
XS GIS Cut Line= 5
 2154099.8575657682451.2109111912154073.50734183682376.821391381
2154089.36347405682252.6150223582154099.93422886681991.869737032
2154096.31501003681897.573573922
#Sta/Elev= 30
       0 1490.43      11 1489.83      35 1489.16      47 1488.55    67.1 1488.85
    86.6 1488.36   110.8 1488.17   151.1 1487.36     191  1487.3   203.6 1486.95
   231.6 1486.59   254.9 1486.86   275.7 1486.72   298.6    1487   351.7 1486.71
     364 1487.03   384.2 1487.03   391.7 1486.84   395.7 1486.54  397.961486.115
   407.7 1483.97   411.7 1483.69   415.7 1483.95  419.621486.115   423.7 1487.85
   427.8 1488.31     451  1488.6   464.1 1488.39   499.8 1489.46   559.5 1494.06
#Mann= 4 ,-1,0
       0     .07       0      20     .05       0  397.96    .045       0
  419.62     .05       0
Bank Sta=397.96,419.62
XS Rating Curve= 0 ,0
Exp/Cntr=0.3,0.1

Type RM Length L Ch R = 1 ,83281   ,129.2,126,119.9
XS GIS Cut Line= 5
     2154138.617      682450.5072154112.26677614 682376.11748019
2154128.12290835682251.9111111672154138.69366316681991.165825841
2154135.07444434681896.869662731
#Sta/Elev= 30
       0 1490.39    39.6  1489.2    48.1 1489.41    56.2  1490.5    60.8 1490.81
    65.1 1490.46      75 1488.77    78.9 1488.42   118.2 1488.12   222.9 1486.65
   258.9 1486.46   270.9  1485.7   278.9 1486.34   287.6 1486.61     355 1486.88
     383 1486.52   407.2 1486.54  412.62 1486.09     415 1485.58   419.7 1483.92
     423 1483.43     427  1483.4   431.1  1483.8  436.441486.095   439.1 1487.15
   447.1 1488.28   475.1 1488.48   487.1 1489.23     508 1491.14   559.5 1492.53
#Mann= 4 ,-1,0
       0     .07       0      20     .05       0  412.62    .045       0
  436.44     .05       0
Bank Sta=412.62,436.44
XS Rating Curve= 0 ,0
Exp/Cntr=0.3,0.1

Type RM Length L Ch R = 1 ,83155   ,181.7,180.3,179.2
XS GIS Cut Line= 4
2154291.58987617682436.0254535472154334.17906693682208.373577381
2154204.76088073681863.4358718812154154.40755731681848.721502065
#Sta/Elev= 30
       0    1490    31.4 1488.39    51.7 1488.47    80.2  1487.7     129 1487.54
   230.8 1487.88   260.5 1487.03   273.5 1486.31   294.8 1486.87   307.6 1486.41
   339.8 1487.16   384.5 1486.56   440.7 1486.52     457    1486   461.4 1485.33
   465.7 1483.79     470  1483.2   474.3 1483.94   478.5  1485.7  480.021485.999
   482.8 1486.53   491.3 1486.76   546.9 1486.09   568.3 1486.47   576.8  1487.4
   589.6 1487.48   600.6 1489.56   604.8 1489.92   613.1 1489.51   652.5 1493.48
#Mann= 4 ,-1,0
       0     .05       0     457    .045       0  480.02     .05       0
  650.02     .08       0
Bank Sta=457,480.02
XS Rating Curve= 0 ,0
Exp/Cntr=0.3,0.1

Type RM Length L Ch R = 1 ,82974   ,508.1,516.8,511.6
XS GIS Cut Line= 4
2154629.63145355682219.7924426872154511.31277023682089.826204072
2154342.13932051681776.6703665452154281.65712383681683.730963168
#Sta/Elev= 30
       0 1505.38    30.6 1504.02    73.9 1500.69     102 1494.86     119 1491.83
   133.1 1489.97   155.8 1488.02   208.3 1486.59   240.1 1486.64     272 1485.77
   331.1 1485.59   367.5 1486.25     372 1486.09   375.9 1485.05   381.1 1483.34
   385.2 1483.75   388.1 1485.03   390.2 1485.98   394.7 1486.69   458.4 1485.19
   485.3 1485.61   499.3 1485.17   512.1 1485.22   531.1 1487.63   542.6 1487.91
   593.1 1492.41   619.5 1493.97   631.3 1494.23   636.8 1495.36   642.6 1497.48
#Mann= 8 ,-1,0
       0     .05       0  275.76      .1       0  345.76     .05       0
   375.9    .045       0   388.1     .05       0  455.76      .1       0
  485.76     .07       0  561.69     .05       0
Bank Sta=375.9,388.1
XS Rating Curve= 0 ,0
Exp/Cntr=0.3,0.1

Type RM Length L Ch R = 1 ,82457   ,164.7,166,155.3
XS GIS Cut Line= 4
2154865.93362279 682047.919709472154857.22310348681937.246167345
2154789.27484751 681653.779643662154769.90137988681554.556162318
#Sta/Elev= 30
       0 1494.22    30.8 1492.38    58.9 1491.06      71 1490.85      79 1490.08
      87 1489.94      99 1488.55   107.1  1488.6   135.8 1487.12   161.7 1486.33
   189.2 1486.59     270 1485.79   283.8 1486.08   324.3 1485.98   337.3 1485.59
   349.7 1486.27  354.391485.282   357.9 1484.23     362 1483.39   366.1 1483.21
   370.2 1483.96  375.281485.281   382.6 1486.46     399 1487.33   417.1 1488.95
   427.6 1490.98   439.8 1494.14   476.5 1501.78   489.2  1503.3   503.6 1504.23
#Mann= 4 ,-1,0
       0     .05       0  354.39    .045       0  375.28     .05       0
  412.51      .1       0
Bank Sta=354.39,375.28
XS Rating Curve= 0 ,0
Exp/Cntr=0.3,0.1

Type RM Length L Ch R = 1 ,82291   ,379.2,380.5,370.3
XS GIS Cut Line= 3
2155241.87909952681994.9648860352155106.87174146 681917.33311754
2154837.84662013681499.698742497
#Sta/Elev= 30
       0 1494.84    43.5 1494.22    66.6 1493.64    75.8 1492.78    94.2 1490.41
   121.9 1488.59   135.8 1488.13   212.8 1487.03   284.4 1486.41   336.7 1485.09
   463.6 1484.87   473.2 1484.73   478.3  1484.2   485.7 1483.87   493.1 1484.15
   500.5 1484.97   503.3 1484.86  505.52 1484.39   508.3 1483.71   512.8 1483.27
   517.5 1483.56   522.7 1484.39     527 1485.11   531.8 1485.45   552.2 1491.79
   579.4 1497.91   593.7 1500.59   603.9 1502.03   640.8 1505.85   652.5 1506.63
#Mann= 6 ,-1,0
       0     .05       0  255.74     .06       0  355.74     .05       0
  475.74      .1       0  505.52    .045       0   522.7      .1       0
Bank Sta=505.52,522.7
XS Rating Curve= 0 ,0
Exp/Cntr=0.3,0.1

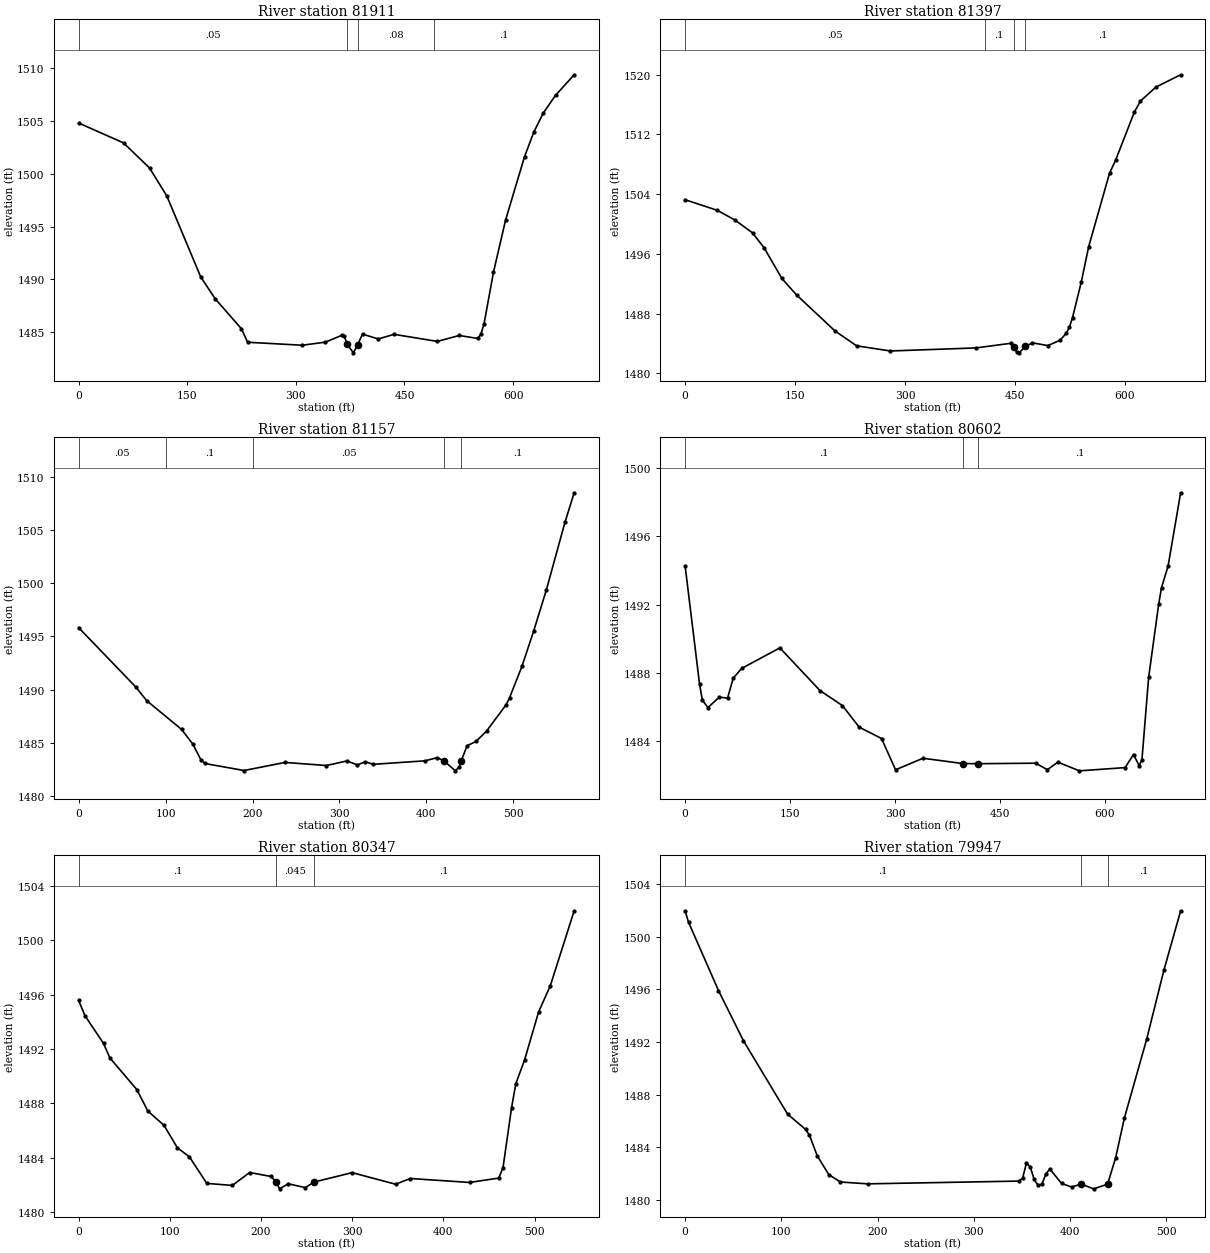
Type RM Length L Ch R = 1 ,81911   ,497.8,513.7,512.4
XS GIS Cut Line= 3
2155429.04200959681740.1902856662155328.03733434681578.590427348
2154868.38002151681398.087694528
#Sta/Elev= 30
       0 1504.79      62 1502.91    97.9 1500.54   121.8 1497.89   168.6 1490.24
   188.6 1488.17   224.8 1485.34   233.4 1484.06   308.8 1483.78   340.8 1484.07
   364.3 1484.74   366.6 1484.69   370.9 1483.86   379.5 1483.06  385.38 1483.84
   392.1 1484.83   413.9 1484.37   435.5 1484.81   495.5 1484.14   525.6  1484.7
   551.4 1484.42   555.7 1484.84     560 1485.83   572.9 1490.67   589.6  1495.6
   615.9 1501.62   628.8 1503.95   641.6 1505.72   658.8 1507.42   684.4 1509.35
#Mann= 4 ,-1,0
       0     .05       0   370.9    .045       0  385.38     .08       0
  490.57      .1       0
Bank Sta=370.9,385.38
XS Rating Curve= 0 ,0
Exp/Cntr(USF)=0,0
Exp/Cntr=0.3,0.1

Type RM Length L Ch R = 1 ,81397   ,239.3,240.1,238.6
XS GIS Cut Line= 3
2155465.56316495681657.1787249222155462.94979749681458.173412196
2155313.80029583681005.109306538
#Sta/Elev= 30
       0 1503.25      44 1501.83      68 1500.53      92 1498.81     108 1496.78
     132  1492.7     152  1490.5   204.3 1485.69   233.9 1483.68   280.1 1482.99
   397.1  1483.4   444.3 1484.02   448.1 1483.58   452.7 1482.82   455.5 1482.74
   464.2 1483.59   473.8 1484.08   494.9 1483.71   511.7 1484.44   520.1 1485.38
   524.3 1486.19   528.5 1487.46   540.5 1492.24   550.5 1496.95     579  1506.8
   587.5  1508.6   612.8 1514.98   621.2 1516.47   642.2 1518.34     676 1519.99
#Mann= 4 ,-1,0
       0     .05       0  409.02      .1       0   448.1    .045       0
   464.2      .1       0
Bank Sta=448.1,464.2
XS Rating Curve= 0 ,0
Exp/Cntr=0.3,0.1

Type RM Length L Ch R = 1 ,81157   ,524,554.9,546.6
XS GIS Cut Line= 3
2155737.04181277681546.8553238122155723.71801275681426.930920269
2155517.43393776681027.784662037
#Sta/Elev= 30
       0 1495.82    66.1 1490.22    78.2 1488.97   118.4 1486.27   131.6 1484.86
   140.6 1483.42   145.1 1483.07   190.2 1482.41   237.4 1483.17   284.9 1482.88
   308.6 1483.31   320.7 1482.93   329.8 1483.24   338.8 1482.99   398.5 1483.32
   412.5 1483.62  420.55  1483.3   433.3 1482.38   437.8 1482.75  440.02  1483.3
   446.8 1484.74   457.1 1485.14   469.3 1486.12   491.8 1488.59   495.7 1489.25
   509.9 1492.18   523.4  1495.5   537.9 1499.33   559.4 1505.71     570 1508.48
#Mann= 5 ,-1,0
       0     .05       0     100      .1       0  200.66     .05       0
  420.55    .045       0  440.02      .1       0
Bank Sta=420.55,440.02
XS Rating Curve= 0 ,0
Exp/Cntr=0.3,0.1

Type RM Length L Ch R = 1 ,80602   ,255.1,255.7,228.8
XS GIS Cut Line= 2
2155900.11781452681585.8445317752155906.97165087680877.838862152
#Sta/Elev= 30
       0 1494.28    20.7  1487.3    24.7 1486.37    32.7 1485.94    48.7 1486.55
    60.7  1486.5    68.7 1487.66    80.7 1488.24   135.4 1489.45   192.7 1486.94
   224.7 1486.06   248.7 1484.79   280.7 1484.12   300.7 1482.28   339.9 1482.96
   396.7 1482.65  419.08 1482.64   500.7 1482.67   517.6 1482.29   532.7 1482.73
   563.3 1482.22   628.7 1482.41   640.7 1483.18   648.7 1482.53   652.7 1482.85
   662.3 1487.71   676.7 1492.03   680.7 1492.99   690.1 1494.26708.0388 1498.57
#Mann= 3 ,-1,0
       0      .1       0   396.7    .045       0  419.08      .1       0
Bank Sta=396.7,419.08
XS Rating Curve= 0 ,0
Exp/Cntr(USF)=0,0
Exp/Cntr=0.3,0.1

Type RM Length L Ch R = 1 ,80347   ,392.1,399,367.6
XS GIS Cut Line= 3
2156208.57017625  681344.1096491 2156190.3356242681231.531110368
2155963.59293352680866.840069407
#Sta/Elev= 30
       0 1495.57       7 1494.44    27.3 1492.41    34.3 1491.34    63.8 1489.02
    75.9 1487.44    93.6 1486.39   108.3 1484.74   121.5 1484.07   140.6 1482.12
   168.6 1481.97   187.5 1482.92     211 1482.63  216.66 1482.23   220.4 1481.72
   229.9 1482.09   248.7 1481.81   258.1 1482.22     300 1482.91   347.6 1482.06
   363.7 1482.48   428.7 1482.19   460.7 1482.51   465.4 1483.26   474.8 1487.68
   479.5 1489.45   489.1  1491.2   504.5 1494.73   517.2 1496.63543.4777 1502.16
#Mann= 3 ,-1,0
       0      .1       0  216.66    .045       0   258.1      .1       0
Bank Sta=216.66,258.1
XS Rating Curve= 0 ,0
Exp/Cntr(USF)=0,0
Exp/Cntr=0.3,0.1

Type RM Length L Ch R = 1 ,79947   ,324.4,330.2,325.2
XS GIS Cut Line= 4
2156457.51145203681252.1440822492156386.15885706681149.079222847
2156356.82501247680896.9667206172156291.02206377680778.045728999
#Sta/Elev= 30
       0 1501.99     3.6 1501.11    34.7 1495.92    60.6  1492.1   106.6  1486.5
   125.2 1485.35   129.3  1484.9   137.3 1483.34   149.4  1481.9   161.5 1481.34
   189.7  1481.2   346.7 1481.41   350.8 1481.63   354.8 1482.78   358.8 1482.49
   362.8 1481.54   366.9 1481.08   370.9 1481.18   374.9 1481.92     379 1482.34
   391.3 1481.23   401.8 1480.96   411.9 1481.18   424.6 1480.82   439.1 1481.17
   447.5 1483.18   456.6 1486.21   479.7 1492.19   497.8  1497.5515.0796 1501.98
#Mann= 3 ,-1,0
       0      .1       0   411.9    .045       0   439.1      .1       0
Bank Sta=411.9,439.1
XS Rating Curve= 0 ,0
Exp/Cntr(USF)=0,0
Exp/Cntr=0.3,0.1

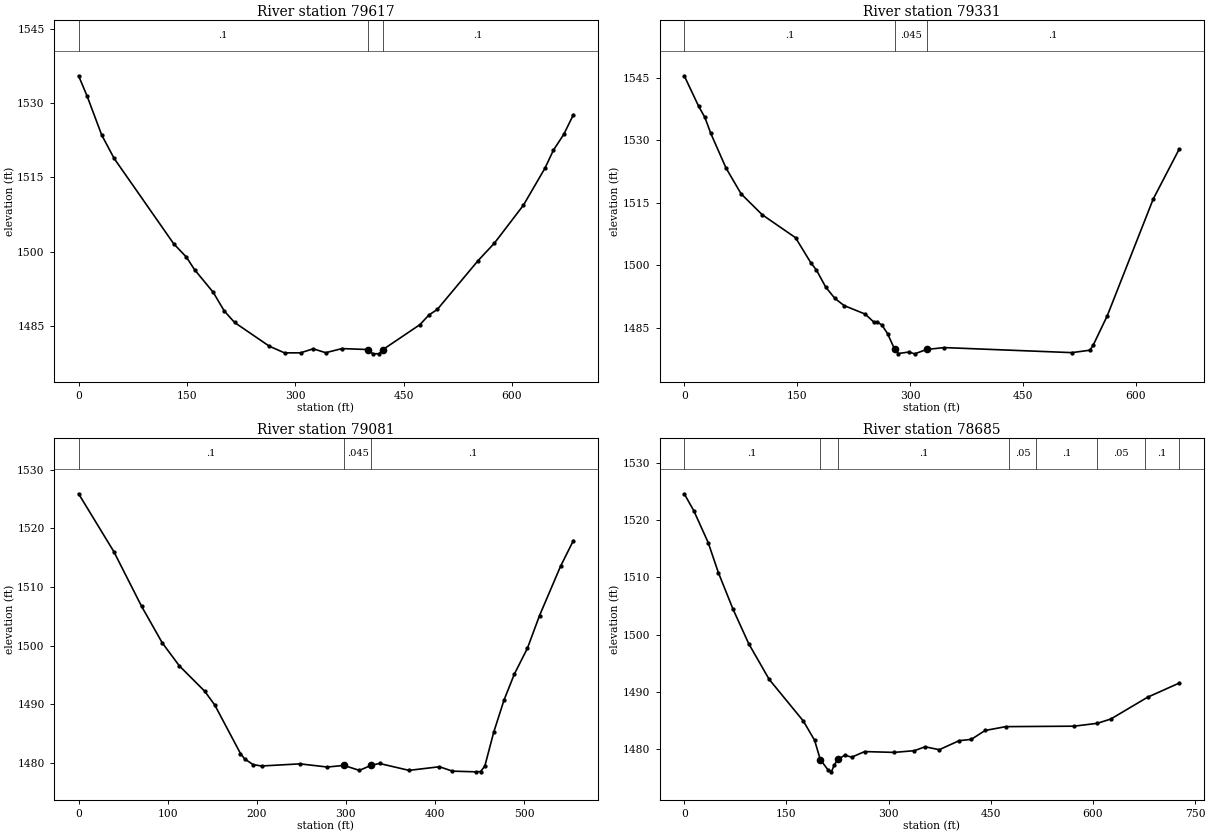
Type RM Length L Ch R = 1 ,79617   ,284.7,286.2,270.3
XS GIS Cut Line= 4
2156849.79745465 681152.320036742156682.15294512681027.526718712
2156577.58872806680783.6444265492156561.40217198680573.574548105
#Sta/Elev= 30
       0 1535.56      12 1531.37    31.9 1523.61    49.1 1518.87   131.7 1501.58
   149.2 1498.89   160.6 1496.34   186.4 1491.76   201.5 1488.02   215.9 1485.67
   264.1 1480.86   285.1 1479.52   307.3 1479.52   324.7 1480.34   342.1 1479.55
   364.6 1480.38  400.66 1480.19   407.4 1479.32   416.1 1479.35  421.441480.192
   472.7 1485.24   484.8 1487.16   496.6  1488.3     553 1498.17   575.5 1501.68
   615.8 1509.38   645.6 1516.86   657.4 1520.53   671.7 1523.71     685 1527.69
#Mann= 3 ,-1,0
       0      .1       0  400.66    .045       0  421.44      .1       0
Bank Sta=400.66,421.44
XS Rating Curve= 0 ,0
Exp/Cntr=0.3,0.1

Type RM Length L Ch R = 1 ,79331   ,234.8,250.5,236
XS GIS Cut Line= 3
2156909.05769094681140.3003570332156883.70096433680882.669005446
2156674.05991041680544.083160847
#Sta/Elev= 30
       0  1545.5    19.2 1538.16    27.3 1535.55    35.3 1531.66    55.4  1523.4
    75.5 1517.18   103.6 1512.16   147.8 1506.66   167.9 1500.71   175.6 1498.88
     188 1494.78   200.1 1492.09   212.2 1490.39   240.3 1488.33   252.3 1486.33
   256.4 1486.42   262.5 1485.71     270 1483.65  279.541479.848   284.2 1478.88
   298.3 1479.23   306.1  1478.8   321.8 1479.85   345.3  1480.3   514.7 1479.09
   538.6 1479.67   542.9 1480.81   561.8 1487.94   622.8 1515.93   657.1 1527.84
#Mann= 3 ,-1,0
       0      .1       0  279.54    .045       0   321.8      .1       0
Bank Sta=279.54,321.8
XS Rating Curve= 0 ,0
Exp/Cntr=0.3,0.1

Type RM Length L Ch R = 1 ,79081   ,349.6,395.6,393.6
XS GIS Cut Line= 3
2157149.75442094680935.3184833132157045.18933359680817.850848918
2156833.10066624680481.039272614
#Sta/Elev= 30
       0 1525.92    39.5 1516.06    70.6 1506.74    93.9 1500.48   113.1 1496.55
   141.5 1492.23   152.8 1489.88   181.7 1481.59   186.4 1480.67   195.9  1479.7
   205.3 1479.47   248.4 1479.83   279.3 1479.29   297.7 1479.57   315.1 1478.72
  328.51 1479.59   337.7  1479.9   370.8 1478.72     405 1479.34   419.5 1478.59
   445.6 1478.47   451.1 1478.51   455.9 1479.45   465.9 1485.24   477.5 1490.74
   489.1 1495.17   503.7 1499.56   517.3 1505.14   540.9 1513.55   555.3 1517.94
#Mann= 3 ,-1,0
       0      .1       0   297.7    .045       0  328.51      .1       0
Bank Sta=297.7,328.51
XS Rating Curve= 0 ,0
Exp/Cntr(USF)=0,0
Exp/Cntr=0.3,0.1

Type RM Length L Ch R = 1 ,78685   ,264,261.1,254.2
XS GIS Cut Line= 4
2157215.05031431680857.0634840752157122.29194085680711.187067691
2157134.97684662680658.8618313792157517.90243963680337.775154012
#Sta/Elev= 30
       0  1524.6    14.1 1521.62    35.2 1516.05    50.1 1510.82    71.5 1504.46
    94.7 1498.39   124.6 1492.18   174.9 1484.87   191.4 1481.51  199.72 1478.14
   211.1 1476.34   216.1    1476   220.2 1477.21   225.8 1478.16   235.6 1478.92
   245.8 1478.56   264.8 1479.54   308.3  1479.4   337.9  1479.7   353.6 1480.38
   374.4 1479.87   403.6 1481.45   421.4 1481.67   441.7 1483.23   472.1  1483.9
   572.3 1483.98   606.4 1484.48   626.3 1485.23   680.2 1489.04726.4395  1491.5
#Mann= 8 ,-1,0
       0      .1       0  199.72    .045       0   225.8      .1       0
  476.71     .05       0  516.71      .1       0  606.71     .05       0
  676.71      .1       0  726.44     .05       0
Bank Sta=199.72,225.8
XS Rating Curve= 0 ,0
Exp/Cntr(USF)=0,0
Exp/Cntr=0.3,0.1