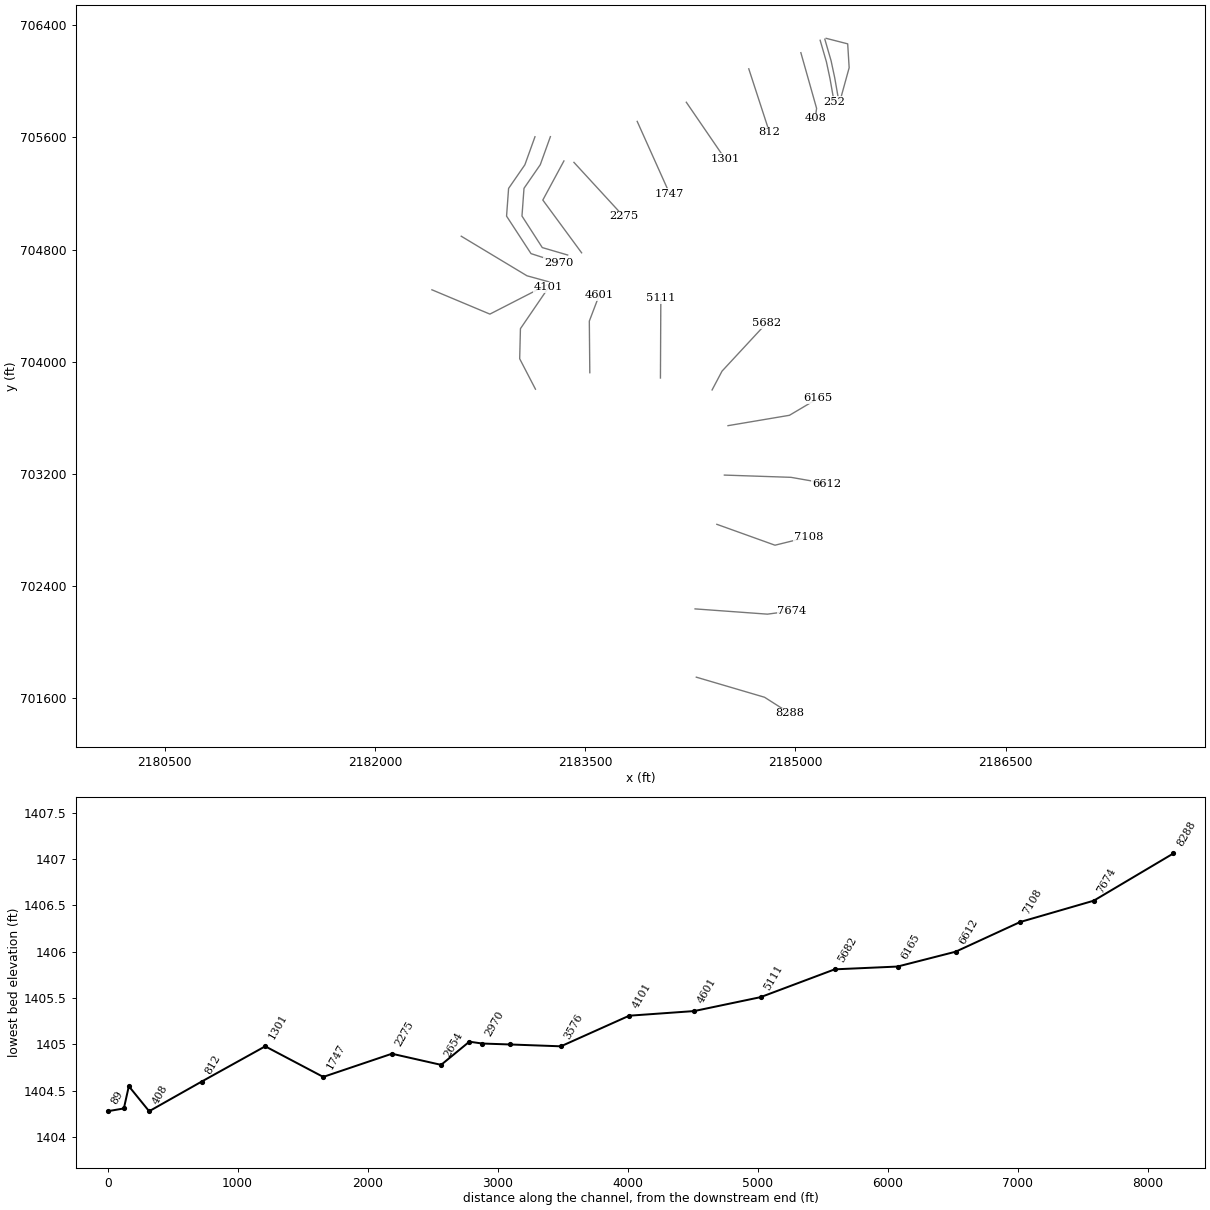
HEC-RAS study FRENCHCK.prj: FRENCHCK

--- FRENCHCK.g01 (geometry) --- (continued)

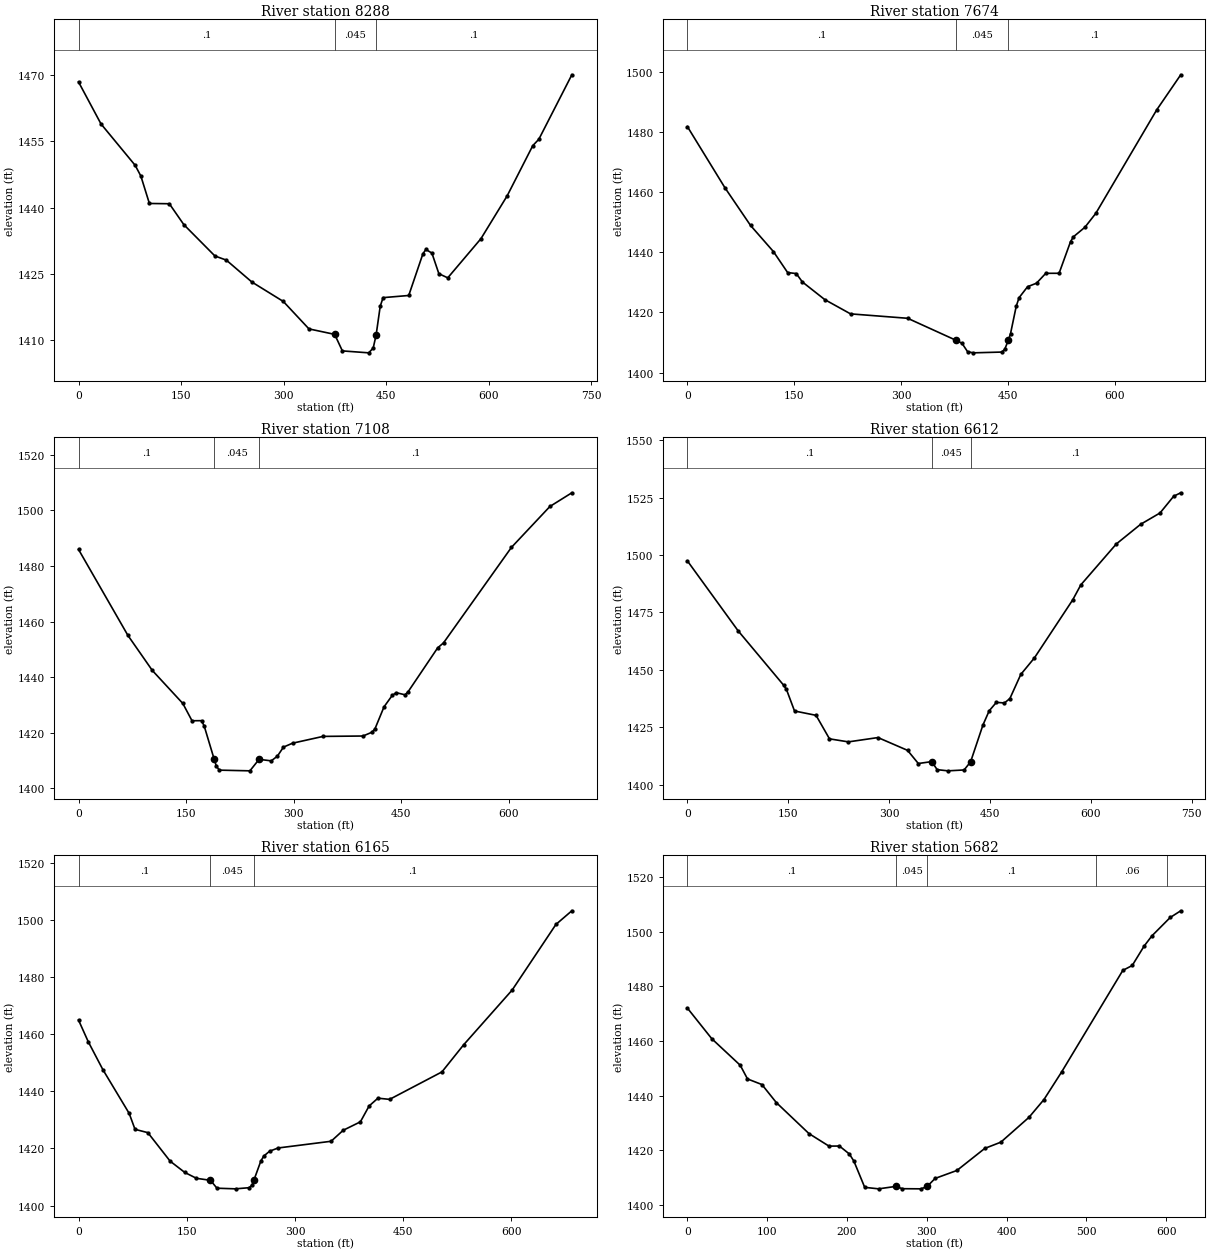
Type RM Length L Ch R = 1 ,8288    ,596.8,613.4,601.5
XS GIS Cut Line= 3
2184292.64811015701749.0433046452184779.41285713701605.789805507
2184960.37428056701490.700027538
#Sta/Elev= 30
       0 1468.51    32.9 1458.98    82.9 1449.59    91.2 1447.17   103.7 1440.94
   132.9 1440.88   154.1 1436.14   199.6 1429.03   216.3 1428.09   253.6 1423.13
   299.7 1418.71   337.2 1412.49   374.8 1411.25   386.1  1407.5   424.6 1407.06
   431.2 1408.14  435.49 1411.12   441.5 1417.65   445.7 1419.58   483.2 1420.07
     504 1429.55   508.3  1430.5   517.1 1429.69   527.3 1425.01   540.3 1424.07
   588.9 1432.96   627.2 1442.66   664.7 1454.05   673.6 1455.51   721.9 1470.13
#Mann= 3 ,-1,0
       0      .1       0   374.8    .045       0  435.49      .1       0
Bank Sta=374.8,435.49
XS Rating Curve= 0 ,0
Exp/Cntr=0.3,0.1

Type RM Length L Ch R = 1 ,7674    ,573,566.4,558.5
XS GIS Cut Line= 3
2184283.81883305702236.2358605842184800.27266264702198.687808959
2184973.50258693702221.762142868
#Sta/Elev= 30
       0 1481.84    52.5 1461.56    88.6 1448.96   120.7 1440.27   140.7 1433.27
   152.8 1432.94   161.4 1430.14   192.9 1424.26     229 1419.52   309.2 1418.05
   377.7 1410.66   385.4 1409.75   393.4 1406.91   401.4 1406.55   441.5 1406.81
   445.5 1407.74  450.49  1410.7   453.6 1412.91   461.6 1422.03   465.6  1424.9
   477.6 1428.57   490.1 1429.73   503.1 1433.02   521.8 1433.03   537.9 1443.57
   541.9 1445.17   558.1 1448.36   573.4    1453   658.8  1487.4   692.6  1499.1
#Mann= 3 ,-1,0
       0      .1       0   377.7    .045       0  450.49      .1       0
Bank Sta=377.7,450.49
XS Rating Curve= 0 ,0
Exp/Cntr=0.3,0.1

Type RM Length L Ch R = 1 ,7108    ,475.1,496,494.8
XS GIS Cut Line= 3
2184439.29263133702839.648524301 2184854.1656184702690.678964325
2185093.84496122702749.750346428
#Sta/Elev= 30
       0 1485.97    68.9 1455.02   102.9 1442.43   145.4 1430.56   158.2 1424.34
   171.5 1424.37   175.2 1422.44   189.2 1410.41   192.2 1407.94   196.4 1406.57
   238.9 1406.32   251.7 1410.46   268.7 1409.91   277.2  1411.6   285.7 1414.86
   298.4 1416.27   340.9 1418.71   396.6 1418.85   409.2 1420.23   413.2 1421.41
   425.9 1429.36   437.3 1433.45   442.9 1434.44   455.2 1433.67   459.4 1434.76
   500.6 1450.55   508.8 1452.36   603.5 1486.72   657.1 1501.43   687.7 1506.36
#Mann= 3 ,-1,0
       0      .1       0   189.2    .045       0   251.7      .1       0
Bank Sta=189.2,251.7
XS Rating Curve= 0 ,0
Exp/Cntr=0.3,0.1

Type RM Length L Ch R = 1 ,6612    ,432.8,446.9,445.2
XS GIS Cut Line= 3
2184492.94638521703190.9921132382184968.08054705703174.947673214
2185222.55720062703130.411831947
#Sta/Elev= 30
       0  1497.4    75.3 1467.01   143.3 1443.22   147.3 1441.43   159.3 1432.06
   191.3 1430.17   211.3 1419.93   239.4 1418.61   283.4 1420.49   327.4 1414.92
   343.4 1409.19   363.4 1410.02   371.4 1406.52   387.4    1406   411.5 1406.38
  421.17 1409.93   439.5 1425.94   448.8 1432.14   459.5 1435.82   471.5 1435.55
   479.6 1437.49   495.8 1447.97   516.1 1455.19     573 1480.43   585.1 1486.97
   637.9 1504.79     674 1513.34   702.9 1518.28   723.2 1525.56   733.7 1527.07
#Mann= 3 ,-1,0
       0      .1       0   363.4    .045       0  421.17      .1       0
Bank Sta=363.4,421.17
XS Rating Curve= 0 ,0
Exp/Cntr=0.3,0.1

Type RM Length L Ch R = 1 ,6165    ,485.2,483,509.7
XS GIS Cut Line= 3
2184518.96304584703543.6608624522184957.15594338703617.567021838
2185163.20191477703739.485195427
#Sta/Elev= 30
       0 1464.96    13.4 1457.41    33.7 1447.61    70.2 1432.27    78.3 1426.68
    96.1 1425.52     127 1415.53   147.3 1411.58   163.5 1409.52   182.9 1408.83
   191.9 1406.06   217.6 1405.84   236.5 1406.24   240.6 1407.17  243.08 1408.87
   252.7 1415.56   256.8 1417.33   264.9 1419.02   276.6 1420.15   350.1  1422.5
   366.8 1426.34   390.7 1429.31   402.8 1434.87     415 1437.59   431.2 1437.18
   503.7 1446.79   533.9 1456.32   601.1 1475.48   661.7 1498.44   683.8 1503.23
#Mann= 3 ,-1,0
       0      .1       0   182.9    .045       0  243.08      .1       0
Bank Sta=182.9,243.08
XS Rating Curve= 0 ,0
Exp/Cntr=0.3,0.1

Type RM Length L Ch R = 1 ,5682    ,568.2,570.5,601.7
XS GIS Cut Line= 3
2184405.36048531703798.6174259992184476.18102277703932.632630925
2184793.54172438704274.906574001
#Sta/Elev= 30
       0 1472.04    30.6 1460.81    66.2  1451.1    75.3 1446.09    93.4 1444.03
   111.5  1437.4   152.3 1426.07   177.4 1421.47   190.5  1421.5   202.9  1418.6
   208.6    1416   222.2 1406.36   239.6 1405.81   261.4 1406.71   269.2 1405.86
   292.8 1405.81  300.52 1406.69   310.4 1409.62   337.8 1412.55   372.7 1420.63
   392.8 1422.91   428.1 1432.02   446.9 1438.55     469 1448.64   545.7 1485.87
   557.5 1487.67   572.3 1494.74   582.2 1498.54   605.1 1505.26   618.3 1507.72
#Mann= 5 ,-1,0
       0      .1       0   261.4    .045       0  300.52      .1       0
  511.58     .06       0  601.58     .07       0
Bank Sta=261.4,300.52
XS Rating Curve= 0 ,0
Exp/Cntr=0.3,0.1

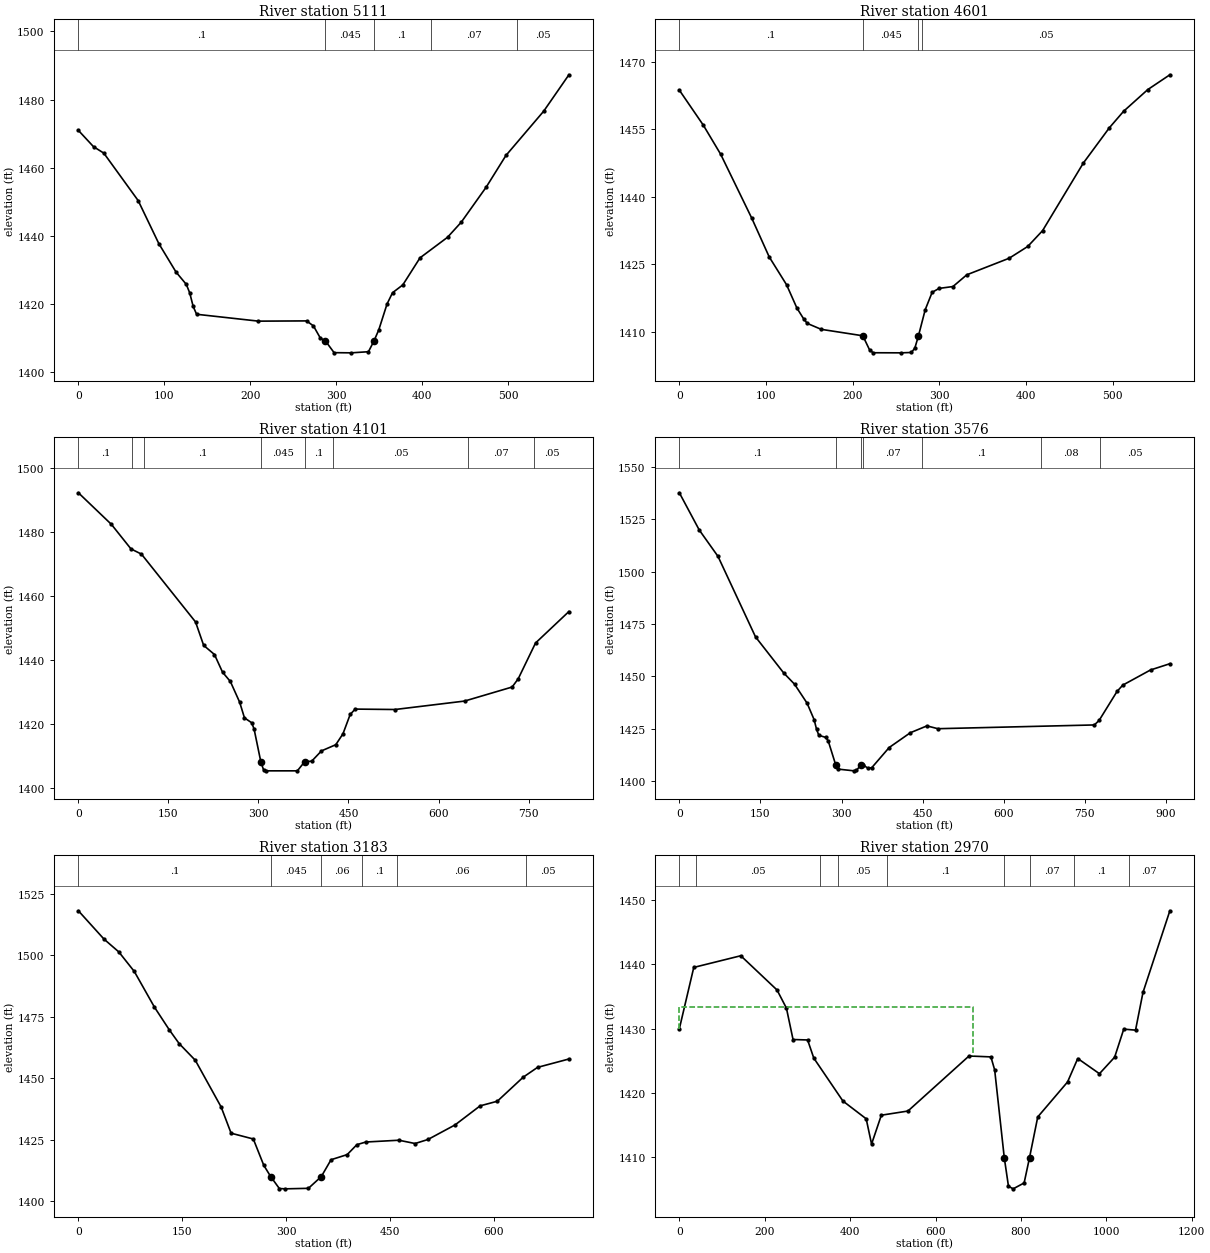
Type RM Length L Ch R = 1 ,5111    ,510,510.9,510.3
XS GIS Cut Line= 2
2184036.75315038 703883.61838046  2184039.565139704454.506428381
#Sta/Elev= 30
       0 1470.92    17.6 1466.13    29.6 1464.23    69.6 1450.27    93.6 1437.64
   113.6 1429.28   125.6 1425.64   129.6 1423.13   133.6 1419.15   137.6 1416.85
   209.6 1414.83   265.6  1414.9   273.6 1413.42   281.6 1409.85   287.6 1408.99
   297.6 1405.56   317.6 1405.51   337.6 1405.84  343.94 1408.96   349.6 1412.25
   359.2 1419.85   365.6 1423.18   377.6 1425.49   397.6 1433.44   429.6 1439.48
   445.6 1443.92   474.7 1454.26   497.6 1463.54   541.6 1476.58   570.9 1487.27
#Mann= 5 ,-1,0
       0      .1       0   287.6    .045       0  343.94      .1       0
     410     .07       0     510     .05       0
Bank Sta=287.6,343.94
XS Rating Curve= 0 ,0
Exp/Cntr=0.3,0.1

Type RM Length L Ch R = 1 ,4601    ,501.6,499.7,498.2
XS GIS Cut Line= 3
2183532.75079269703921.4440593052183529.32621869704289.700576382
2183599.80653819704474.489341475
#Sta/Elev= 30
       0  1463.7    27.7 1455.91    47.7 1449.46    83.7 1435.21   103.7 1426.66
   123.7 1420.49   135.7 1415.29   143.7 1412.83   147.7 1411.89   163.7 1410.58
   211.7 1409.15   219.7 1405.94   223.7 1405.38   255.7 1405.36   267.7 1405.44
   271.7 1406.39  275.94 1409.15   283.7 1414.93   291.7  1418.8   299.7 1419.67
   315.7 1420.08   331.7 1422.69   380.6 1426.37     402 1428.98   419.1 1432.49
   466.1 1447.49   496.1 1455.32   512.6    1459   540.5 1463.82     566 1467.11
#Mann= 4 ,-1,0
       0      .1       0   211.7    .045       0  275.94      .1       0
     280     .05       0
Bank Sta=211.7,275.94
XS Rating Curve= 0 ,0
Exp/Cntr=0.3,0.1

Type RM Length L Ch R = 1 ,4101    ,579.1,525.4,472.1
XS GIS Cut Line= 4
2183145.01301548703803.9241101522183032.41252059 704020.96879372
 2183037.7812599704235.7691256352183239.55022437704531.285984518
#Sta/Elev= 30
       0 1492.27      55 1482.39    87.6 1474.72   105.1 1473.08   195.2 1451.87
   208.7 1444.55   226.7 1441.69   240.2 1436.15   253.2 1433.25   268.7 1426.77
   276.7 1421.87   288.7 1420.35   292.7  1418.4  303.98 1408.11   308.7 1405.51
   312.7 1405.31   364.8 1405.31   376.8 1408.12   388.8 1408.35     405 1411.55
   428.8 1413.48   440.8 1416.89   452.8 1422.94   461.1 1424.62   527.5 1424.49
   643.4 1427.13   722.6 1431.52   732.7 1434.08   761.6 1445.29   817.2 1455.13
#Mann= 8 ,-1,0
       0      .1       0      90     .08       0     110      .1       0
  303.98    .045       0   376.8      .1       0  424.51     .05       0
  649.38     .07       0  759.38     .05       0
Bank Sta=303.98,376.8
XS Rating Curve= 0 ,0
Exp/Cntr=0.3,0.1

Type RM Length L Ch R = 1 ,3576    ,395.3,392.6,387.5
XS GIS Cut Line= 3
2182406.23013655704513.0805880712182819.84185529704339.642021987
2183228.04177234704548.922073153
#Sta/Elev= 30
       0 1537.67    36.8 1519.92    71.5 1507.32   140.9  1468.9     193 1451.69
     213 1446.35   236.3 1437.25   249.3 1429.39   253.7 1424.86     258 1421.93
     271 1420.92   275.4 1419.22  289.28 1407.76   292.7 1405.83   323.1 1404.98
   327.4 1405.16   336.1 1407.88     340 1407.79   349.1 1406.18   355.9 1406.49
   388.1 1416.11   427.2 1423.16   457.9 1426.43   478.2 1425.09   767.5 1426.88
   776.3 1429.01   809.5 1442.87   820.1 1445.88   871.4 1453.11   907.2  1456.1
#Mann= 7 ,-1,0
       0      .1       0  289.28    .045       0   336.1      .1       0
     340     .07       0   448.5      .1       0   668.5     .08       0
   778.5     .05       0
Bank Sta=289.28,336.1
XS Rating Curve= 0 ,0
Exp/Cntr=0.3,0.1

Type RM Length L Ch R = 1 ,3183    ,219.5,212.5,191.7
XS GIS Cut Line= 3
2182615.46880071704895.303744877 2183084.2975753704613.106495394
2183239.94037451704570.234618349
#Sta/Elev= 30
       0 1518.08      37 1506.56    58.4 1501.35    80.8 1493.39   109.9 1478.88
   131.5 1469.59   145.6 1464.06   168.9 1457.28   206.2  1438.3   220.6 1427.63
   252.7 1425.27   267.8 1414.58   277.81409.985   290.3 1405.13   298.9    1405
   332.3 1405.21  350.921409.987     365 1416.84   388.3 1418.92   402.3 1422.96
   415.2 1424.04     463 1424.77   486.4 1423.43     505 1425.07   544.2 1431.01
   580.3 1438.74   605.2 1440.63   642.5 1450.39   663.3  1454.4   708.6  1457.8
#Mann= 6 ,-1,0
       0      .1       0   277.8    .045       0  350.92     .06       0
     410      .1       0     460     .06       0  647.21     .05       0
Bank Sta=277.8,350.92
XS Rating Curve= 0 ,0
Exp/Cntr=0.3,0.1

Type RM Length L Ch R = 1 ,2970    ,100.5,99.1,92.1
XS GIS Cut Line= 6
2183141.52283892705605.0698279022183069.49088108705405.051248708
2182953.23548694 705236.461624932182938.82881533705038.605220786
2183113.23553766 704771.264353022183309.75589157704707.530325714
#Sta/Elev= 30
       0 1429.96    33.8 1439.53   143.9 1441.35   228.8 1436.01   250.8 1433.18
   266.3 1428.29   300.4 1428.22   314.9 1425.39   383.1  1418.7   437.6 1415.93
   450.2 1411.99   473.1 1416.49   535.4 1417.14   678.4 1425.72   729.7 1425.58
   738.5 1423.55  760.991409.869   770.8 1405.42   781.8 1405.01   807.5 1405.93
   820.11409.865   839.4 1416.22   909.2 1421.67   933.1 1425.33   983.9 1422.96
  1019.5 1425.54  1040.8 1429.91  1068.4 1429.75  1085.8 1435.62  1148.8 1448.36
#Mann= 9 ,-1,0
       0      .1       0      40     .05       0  328.31     .06       0
  371.75     .05       0   485.9      .1       0  760.99    .045       0
   820.1     .07       0   924.6      .1       0 1052.12     .07       0
#XS Ineff= 2 , 0
           688.9 1433.35
Permanent Ineff=
       F       F
Bank Sta=760.99,820.1
XS Rating Curve= 0 ,0
Exp/Cntr=0.3,0.1

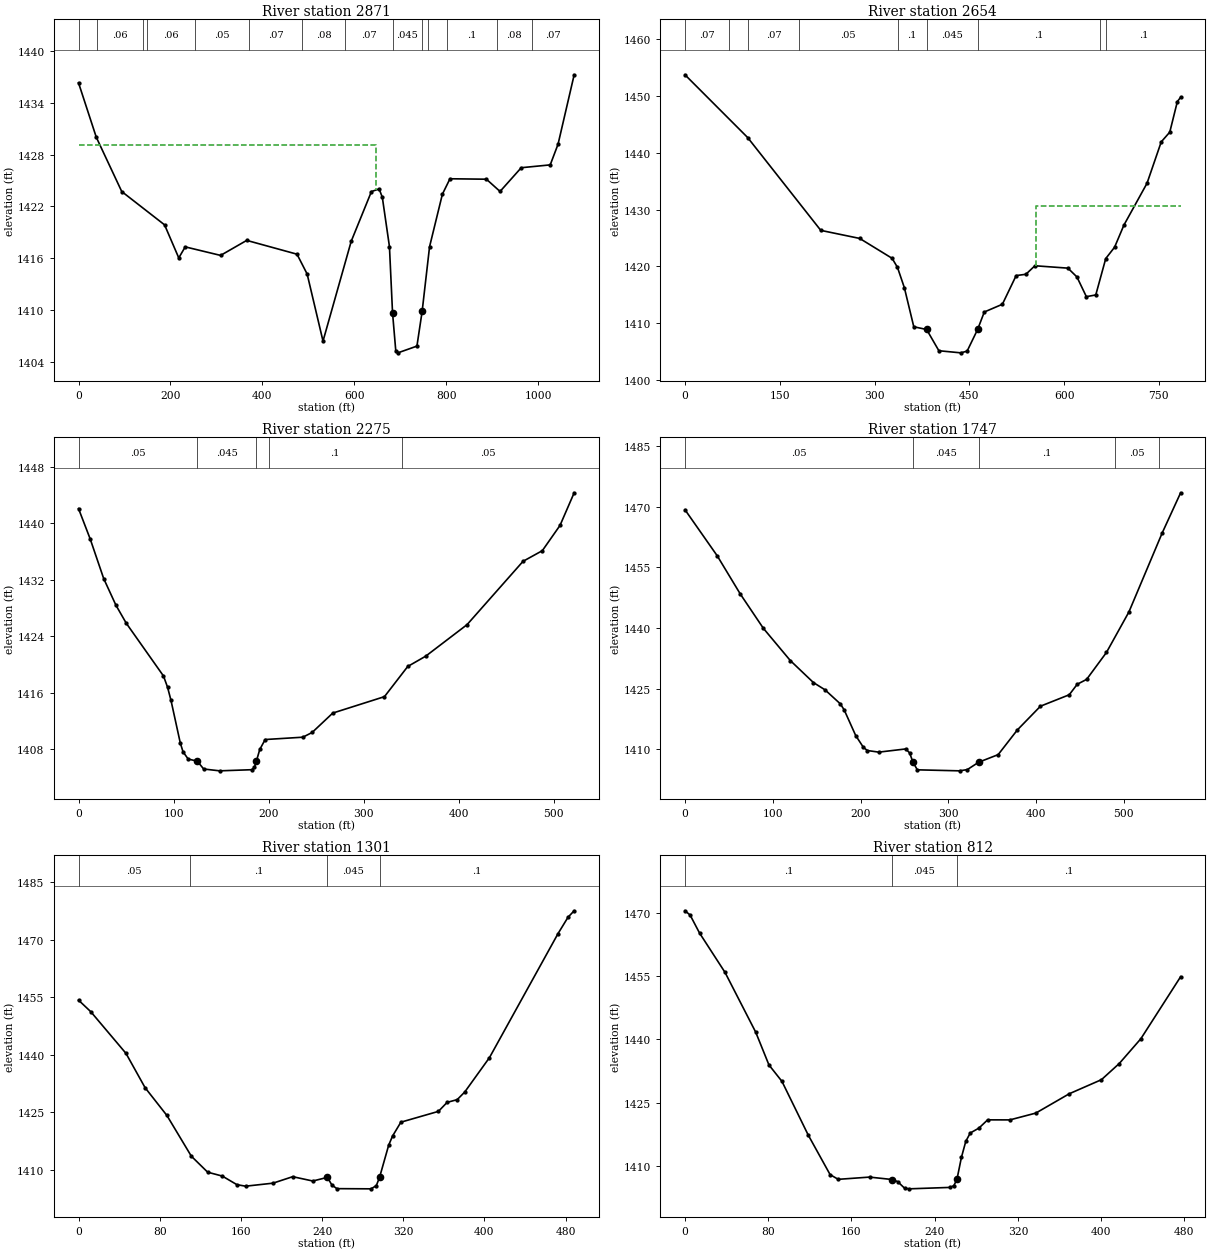
Type RM Length L Ch R = 1 ,2871    ,206.7,217.2,214.9
XS GIS Cut Line= 6
2183251.46657559705605.7359955062183179.43461774705405.717416311
2183063.17922361705237.127792533  2183048.772552705039.271388389
2183193.70513673704814.2836846742183374.74520486704761.235460581
#Sta/Elev= 30
       0 1436.32    38.7 1430.01    94.1 1423.72   187.3 1419.86   218.2 1416.03
   232.2 1417.31   309.2 1416.32   366.1 1418.06   475.5 1416.46   497.6 1414.16
   532.1 1406.39   593.5 1417.96   637.5 1423.72   654.3 1424.02   661.2 1423.05
   676.7 1417.34  683.41 1409.68   690.5 1405.24   695.1 1405.03   736.5 1405.81
  747.861409.842     764 1417.33   791.9 1423.41   808.4  1425.2   887.7 1425.15
   917.4 1423.73   963.5 1426.48  1026.6 1426.81  1043.6  1429.2  1078.7 1437.25
#Mann= 14 ,-1,0
       0     .05       0      40     .06       0     140     .05       0
     150     .06       0  252.64     .05       0  371.75     .07       0
   485.9     .08       0  580.48     .07       0  683.41    .045       0
  747.86     .07       0   759.8     .08       0  801.59      .1       0
  909.78     .08       0  987.08     .07       0
#XS Ineff= 2 , 0
          648.34 1429.14
Permanent Ineff=
       F       F
Bank Sta=683.41,747.86
XS Rating Curve= 0 ,0
Exp/Cntr=0.3,0.1

Type RM Length L Ch R = 1 ,2654    ,371.5,378.6,378
XS GIS Cut Line= 3
2183348.04896556705432.4848347712183197.49215992705153.457860929
2183474.33053634704776.989989855
#Sta/Elev= 30
       0 1453.73    99.2 1442.68   214.9 1426.34   276.5 1424.92   327.8 1421.42
   336.3 1419.82   347.2 1416.24   362.1 1409.37   382.4 1408.89   401.8 1405.15
   436.4 1404.78   446.5 1405.08  463.13  1408.9   473.7 1411.97   502.3 1413.33
   524.1 1418.38   539.5 1418.61   553.8 1420.11     606 1419.69   620.3 1418.14
   635.2 1414.67   650.1 1414.97   665.9 1421.38   679.9 1423.38   694.7 1427.28
   731.2 1434.63   753.7 1441.92   767.2 1443.63   779.2 1449.01   784.4 1449.77
#Mann= 9 ,-1,0
       0     .07       0      70     .05       0     100     .07       0
     180     .05       0  337.05      .1       0   382.4    .045       0
  463.13      .1       0  657.05     .07       0  667.05      .1       0
#XS Ineff= 2 , 0
                          555.83         1430.62
Permanent Ineff=
       F       F
Bank Sta=382.4,463.13
XS Rating Curve= 0 ,0
Exp/Cntr=0.3,0.1

Type RM Length L Ch R = 1 ,2275    ,525.9,528.1,503.1
XS GIS Cut Line= 2
2183419.67958003705422.1673132742183772.56124439705038.157788325
#Sta/Elev= 30
       0 1442.09    12.4 1437.74    26.5 1432.16    39.4 1428.38    50.2 1425.84
    89.4 1418.35    93.7 1416.75    97.3 1414.89   107.1 1408.84     110 1407.59
   115.4 1406.57   124.9 1406.28   131.7 1405.16   148.5  1404.9   182.2 1405.06
   185.1 1405.39  187.18 1406.29   190.7 1407.93   196.4 1409.34     236 1409.67
   245.8 1410.34   267.5 1413.09   321.9 1415.42   346.4  1419.7   365.3 1421.16
   408.8 1425.63   467.7 1434.61     488 1436.12   506.6  1439.7   521.5 1444.33
#Mann= 5 ,-1,0
       0     .05       0   124.9    .045       0  187.18     .05       0
     200      .1       0     340     .05       0
Bank Sta=124.9,187.18
XS Rating Curve= 0 ,0
Exp/Cntr=0.3,0.1

Type RM Length L Ch R = 1 ,1747    ,438.8,446.4,448.2
XS GIS Cut Line= 2
2183870.92476934705714.6528089592184102.15198792705199.497173858
#Sta/Elev= 30
       0 1469.28    36.7 1457.89      63 1448.43    89.3 1439.93     120 1431.95
   146.3 1426.51   159.5 1424.71     177 1421.23   181.4 1419.73   194.5 1413.39
   203.3 1410.45   207.8 1409.68   220.8 1409.28   251.5 1410.07   255.9  1409.1
  259.68 1406.84   264.7  1404.9   312.9 1404.65   321.7 1404.96   334.6 1406.78
   356.8 1408.66   378.7 1414.78     405 1420.65   437.8 1423.48   446.9 1426.08
   457.6 1427.29   480.2 1433.96   505.8 1443.99   543.7 1463.54   564.7 1473.48
#Mann= 5 ,-1,0
       0     .05       0  259.68    .045       0   334.6      .1       0
     490     .05       0     540      .1       0
Bank Sta=259.68,334.6
XS Rating Curve= 0 ,0
Exp/Cntr=0.3,0.1

Type RM Length L Ch R = 1 ,1301    ,489.1,488.7,476.1
XS GIS Cut Line= 2
2184221.33168098705851.3432038322184497.29172972705448.241055076
#Sta/Elev= 30
       0 1454.19    12.1 1451.17    46.8  1440.3    65.6 1431.36    87.1 1424.12
   111.2 1413.49   127.3 1409.32   141.7 1408.31   156.1 1406.07   164.7 1405.67
   191.7 1406.46   211.1 1408.15   230.9 1407.02   245.3 1407.97   249.8 1405.94
   254.7 1405.03   288.3 1404.98   293.5 1405.82  296.72 1407.99   305.7 1416.38
   309.5 1418.74   317.7 1422.36   354.7 1425.18   363.3 1427.53   373.2 1428.24
   380.6 1430.21     405 1439.19   472.6 1471.54   482.5 1475.83   488.5 1477.49
#Mann= 4 ,-1,0
       0     .05       0     110      .1       0   245.3    .045       0
  296.72      .1       0
Bank Sta=245.3,296.72
XS Rating Curve= 0 ,0
Exp/Cntr=0.3,0.1

Type RM Length L Ch R = 1 ,812     ,393.7,404.2,387.5
XS GIS Cut Line= 2
2184667.09794396706089.8100747242184814.66237432705636.856506384
#Sta/Elev= 30
       0 1470.42     4.9 1469.42      14 1465.15    38.5 1455.83      68 1441.68
    80.7 1433.93    93.2 1430.04   118.5 1417.31   139.5 1407.96   147.3 1406.85
   177.4 1407.38     199 1406.81   204.4 1406.31     211 1404.77   215.2  1404.6
   255.1 1404.94   258.4 1405.36  261.39 1406.83   265.7 1412.04   269.9 1415.84
   274.2 1417.82   282.5 1418.97   290.9 1420.93   312.3 1420.92   337.2 1422.53
   369.4 1427.11   400.3 1430.44   417.4 1434.26   438.2 1440.14   476.4 1454.81
#Mann= 3 ,-1,0
       0      .1       0     199    .045       0  261.39      .1       0
Bank Sta=199,261.39
XS Rating Curve= 0 ,0
Exp/Cntr=0.3,0.1

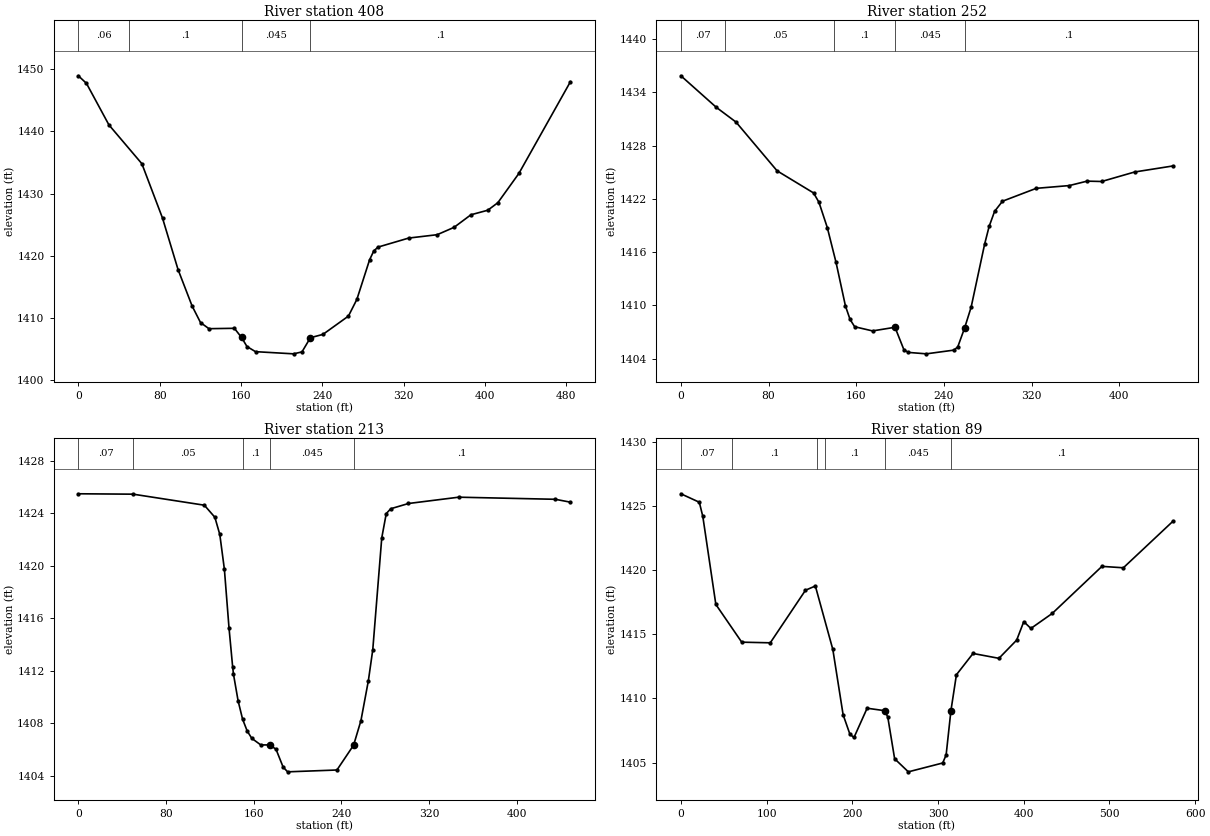
Type RM Length L Ch R = 1 ,408     ,157.7,156.3,153.3
XS GIS Cut Line= 3
2185038.74032452 706204.867164162185150.96436402705807.694050783
2185141.32150039705736.979717506
#Sta/Elev= 30
       0 1448.93       8 1447.71    30.1 1441.04    62.5 1434.81    82.8 1426.08
    98.1 1417.81   111.9 1411.97   120.2  1409.3   128.5 1408.32   153.5 1408.38
  160.56 1406.91   165.9 1405.45   174.3 1404.63   211.7 1404.28     220 1404.59
   228.3 1406.87   240.6  1407.4   265.7 1410.34     274 1413.02   286.5 1419.37
   290.6 1420.79   294.8 1421.42     325 1422.87     353 1423.41   369.6 1424.59
   386.2 1426.61   402.8 1427.34   412.7 1428.55   433.4 1433.25  484.09 1447.98
#Mann= 4 ,-1,0
       0     .06       0      50      .1       0  160.56    .045       0
   228.3      .1       0
Bank Sta=160.56,228.3
XS Rating Curve= 0 ,0
Exp/Cntr=0.3,0.1

Type RM Length L Ch R = 1 ,252     ,40.3,38.2,35.2
XS GIS Cut Line= 4
2185176.33266547706293.4421960762185220.97555264706139.870664212
 2185246.8684272706018.4420111112185275.43987499705855.941901814
#Sta/Elev= 30
       0 1435.85    32.4 1432.29    50.3 1430.64    87.8 1425.15   121.1 1422.66
     126 1421.61   133.6 1418.77   141.6 1414.84   150.2 1409.93   154.4 1408.42
   158.6  1407.6   174.9 1407.13   195.4 1407.54   203.6 1404.99   207.7 1404.71
     224 1404.55   249.2 1404.97   252.7 1405.34  258.87 1407.44   264.9 1409.81
   277.2  1416.9   281.3 1418.89   286.3 1420.59   293.5 1421.73   324.3 1423.18
   354.4 1423.49   370.7 1423.99     384 1423.95   414.1 1425.02  449.08  1425.7
#Mann= 5 ,-1,0
       0     .07       0      40     .05       0     140      .1       0
   195.4    .045       0  258.87      .1       0
Bank Sta=195.4,258.87
XS Rating Curve= 0 ,0
Exp/Cntr=0.3,0.1

Type RM Length L Ch R = 1 ,213     ,133.1,124.8,122.1
XS GIS Cut Line= 4
2185209.67420796706301.1559677992185254.31709513706147.584435935
2185280.20996968706026.1557828342185308.78141747705863.655673536
#Sta/Elev= 30
       0 1425.49      50 1425.46     115 1424.62   124.6  1423.7   129.1 1422.39
   133.3 1419.73   137.5 1415.28   140.8 1412.33   141.6 1411.74   145.8 1409.72
   149.9 1408.32   154.1 1407.42   158.3 1406.86   166.5 1406.36   174.7 1406.36
   180.4 1406.03   186.9 1404.67     191 1404.31     236 1404.45   251.2 1406.34
   257.9 1408.21   264.7 1411.26   268.7 1413.61   276.9 1422.13     281 1423.98
   285.1 1424.35   301.3 1424.75   347.1 1425.23   435.3 1425.07  449.08 1424.85
#Mann= 5 ,-1,0
       0     .07       0      50     .05       0     150      .1       0
   174.7    .045       0   251.2      .1       0
Bank Sta=174.7,251.2
XS Rating Curve= 0 ,0
Exp/Cntr=0.3,0.1

Type RM Length L Ch R = 1 ,89      ,,,
XS GIS Cut Line= 4
2185219.37733728706307.3261339862185372.85958337706267.951107502
2185383.30601896706097.5938500632185318.21668947705861.343691161
#Sta/Elev= 30
       0 1425.96    21.5  1425.3    25.6 1424.19    40.8 1417.33      71 1414.39
   104.3 1414.34   145.4 1418.44   156.9 1418.77   177.3 1413.82   189.3 1408.73
   197.3  1407.2     202 1406.96   217.3 1409.24  237.63 1409.05   241.4 1408.56
   249.4  1405.3   265.4 1404.28   305.5 1404.97   309.5  1405.6   315.11409.052
   321.5 1411.85   340.9 1413.51   371.1 1413.13   391.8 1414.55   400.1 1415.99
   408.4 1415.46   433.3 1416.63   491.3  1420.3   516.3 1420.19  574.18 1423.82
#Mann= 6 ,-1,0
       0     .07       0      60      .1       0  158.45     .06       0
  168.45      .1       0  237.63    .045       0   315.1      .1       0
Bank Sta=237.63,315.1
XS Rating Curve= 0 ,0
Exp/Cntr=0.3,0.1
LCMann Table=0

Chan Stop Cuts=-1
Use User Specified Reach Order=0
Composite Channel Slope=5